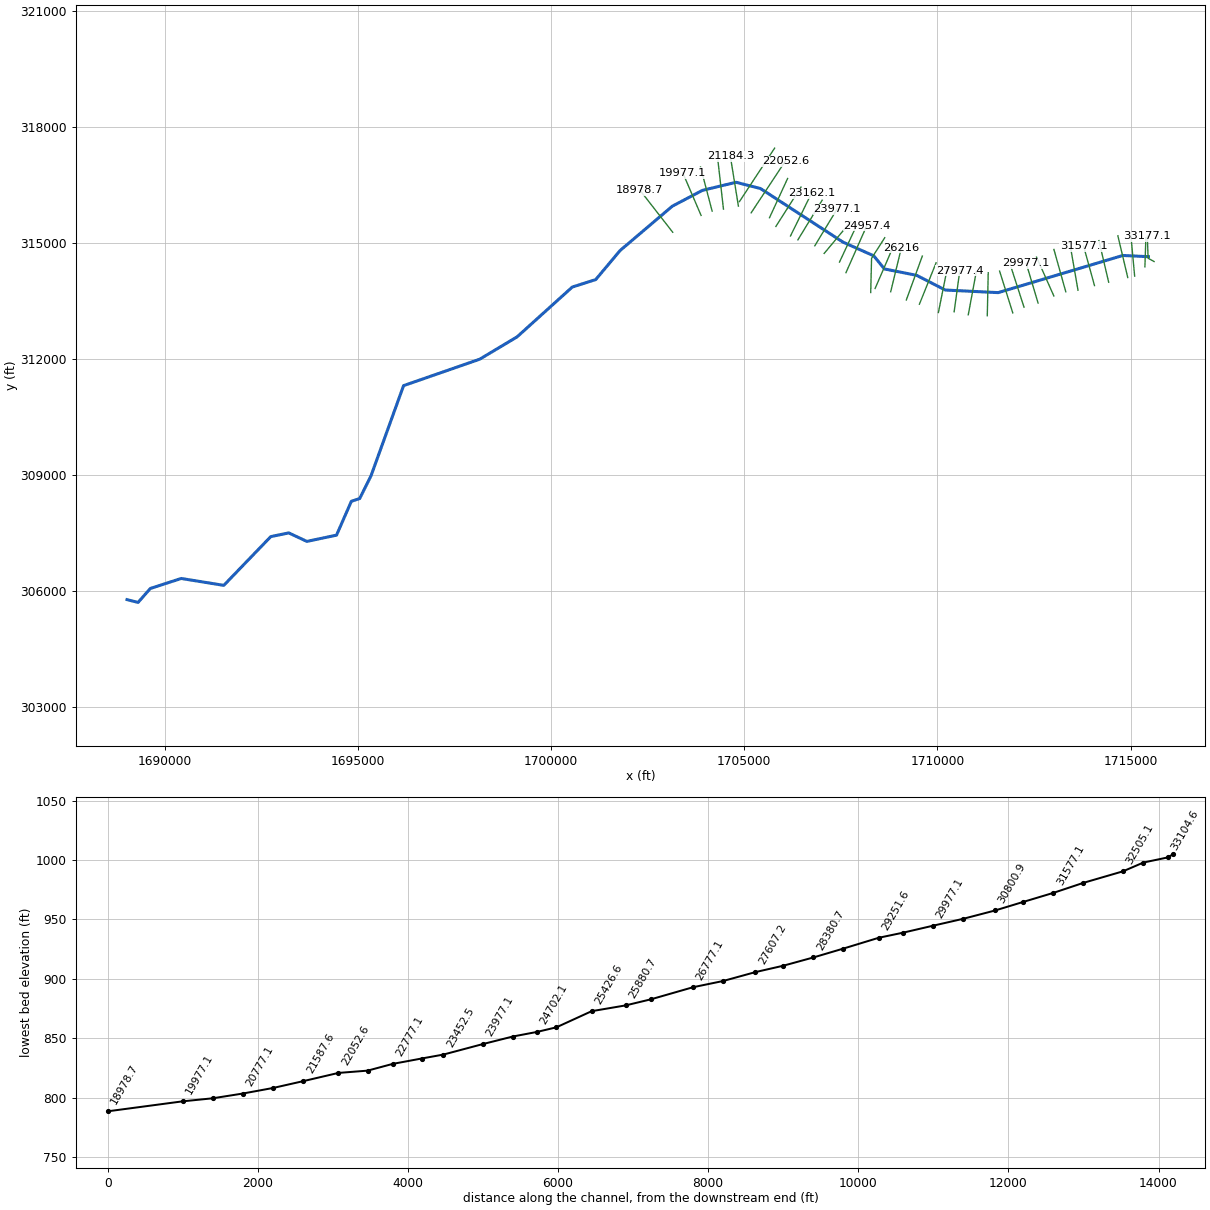
--- DINGESSRN.prj (project) ---

Proj Title=DINGESSRN
Current Plan=p01
Default Exp/Contr=0,0
English Units
Geom File=g01
Flow File=f01
Plan File=p01
BEGIN DESCRIPTION:
END DESCRIPTION:
DSS Export Rating Curves= 0
DSS Export Rating Curve Sorted= 0
DSS Export Volume Flow Curves= 0
DXF OffsetX= 0
DXF OffsetY= 0
DXF ScaleX= 0
DXF ScaleY= 0

--- DINGESSRN.p01 (plan) ---

Plan Title=Floodplain
Program Version=4.00
Geom File=g01
Flow File=f01
K Sum by GR=0
Std Step Tol=0.01
Critical Tol=0.01
Num of Std Step Trials=20
Max Error Tol=0.3
Flow Tol Ratio=0.001
Split Flow NTrial=30
Split Flow Tol=0.02
Split Flow Ratio=0.02
Log Output Level=0
Friction Slope Method=1
Unsteady Friction Slope Method=2
Unsteady Bridges Friction Slope Method=1
Global Log Level=0
CheckData=False
Run HTab=0
Run UNet=0
Run PostProcess=0
UNET Theta=0
UNET Theta Warmup=0
UNET ZTol=0
UNET ZSATol=0
UNET MxIter=0
UNET MaxInSteps=0
UNET DtIC=0
UNET DtMin=0
UNET MaxCRTS=0
UNET WFStab=0
UNET SFStab=0
UNET WFX=0
UNET SFX=0
UNET DSS MLevel=0
UNET DZMax Abort=0
UNET Convert EG Bridges=0
UNET Use Existing IB Tables=0
UNET Froude Limit=0
UNET Froude Power=0
Write IC File=0
Echo Input=False
Echo Output=False
Write Detailed=0

--- DINGESSRN.f01 (steady flow) ---

Flow Title=NFF Regression Equation
Program Version=4.00
Number of Profiles=1
Profile Names=P100yr
River Rch & RM=DINGESSRN,Main      ,33177.1
976.4719
River Rch & RM=DINGESSRN,Main      ,32777.1
1417.894
River Rch & RM=DINGESSRN,Main      ,31177.1
1481.711
River Rch & RM=DINGESSRN,Main      ,24957.4
1639.117
River Rch & RM=DINGESSRN,Main      ,24702.1
2027.525
River Rch & RM=DINGESSRN,Main      ,21587.6
2233.559
River Rch & RM=DINGESSRN,Main      ,21184.3
3082.446
River Rch & RM=DINGESSRN,Main      ,18392.3
3418.373
River Rch & RM=DINGESSRN,Main      ,15855.5
3650.316
River Rch & RM=DINGESSRN,Main      ,7645.4
3984.770
River Rch & RM=DINGESSRN,Main      ,6830.8
4600.103
River Rch & RM=DINGESSRN,Main      ,823
4695.627
Boundary for River Rch & Prof#=DINGESSRN,Main      ,1
Up Type=0
Dn Type=3
Dn Slope=0.002309

--- DINGESSRN.g01 (geometry) ---

Geom Title=USGS 10m DEM
Program Version=4.10

River Reach=DINGESSRN       ,Main
Reach XY= 30
     1715461.372      314652.537      1714798.88      314683.808
     1711572.126      313722.499      1710203.13      313789.675
     1709463.038      314169.566     1708627.974      314335.189
     1708350.005      314675.701     1707557.794      315027.794
     1705418.593       316416.48     1704787.372       316577.47
     1703917.562      316368.994     1703138.396      315959.759
     1701783.298      314809.664     1701155.552      314060.306
     1700548.654      313866.886     1699118.273      312576.648
     1698152.332      311999.863      1696181.07      311315.365
     1695339.056      308983.902     1695046.031      308394.377
     1694829.447      308322.568     1694446.081      307446.966
     1693678.193      307284.818     1693209.121      307504.877
     1692743.523      307408.746      1691527.41      306147.462
     1690425.959      306325.826     1689625.932      306066.568
     1689308.842      305706.238     1689022.637      305778.304

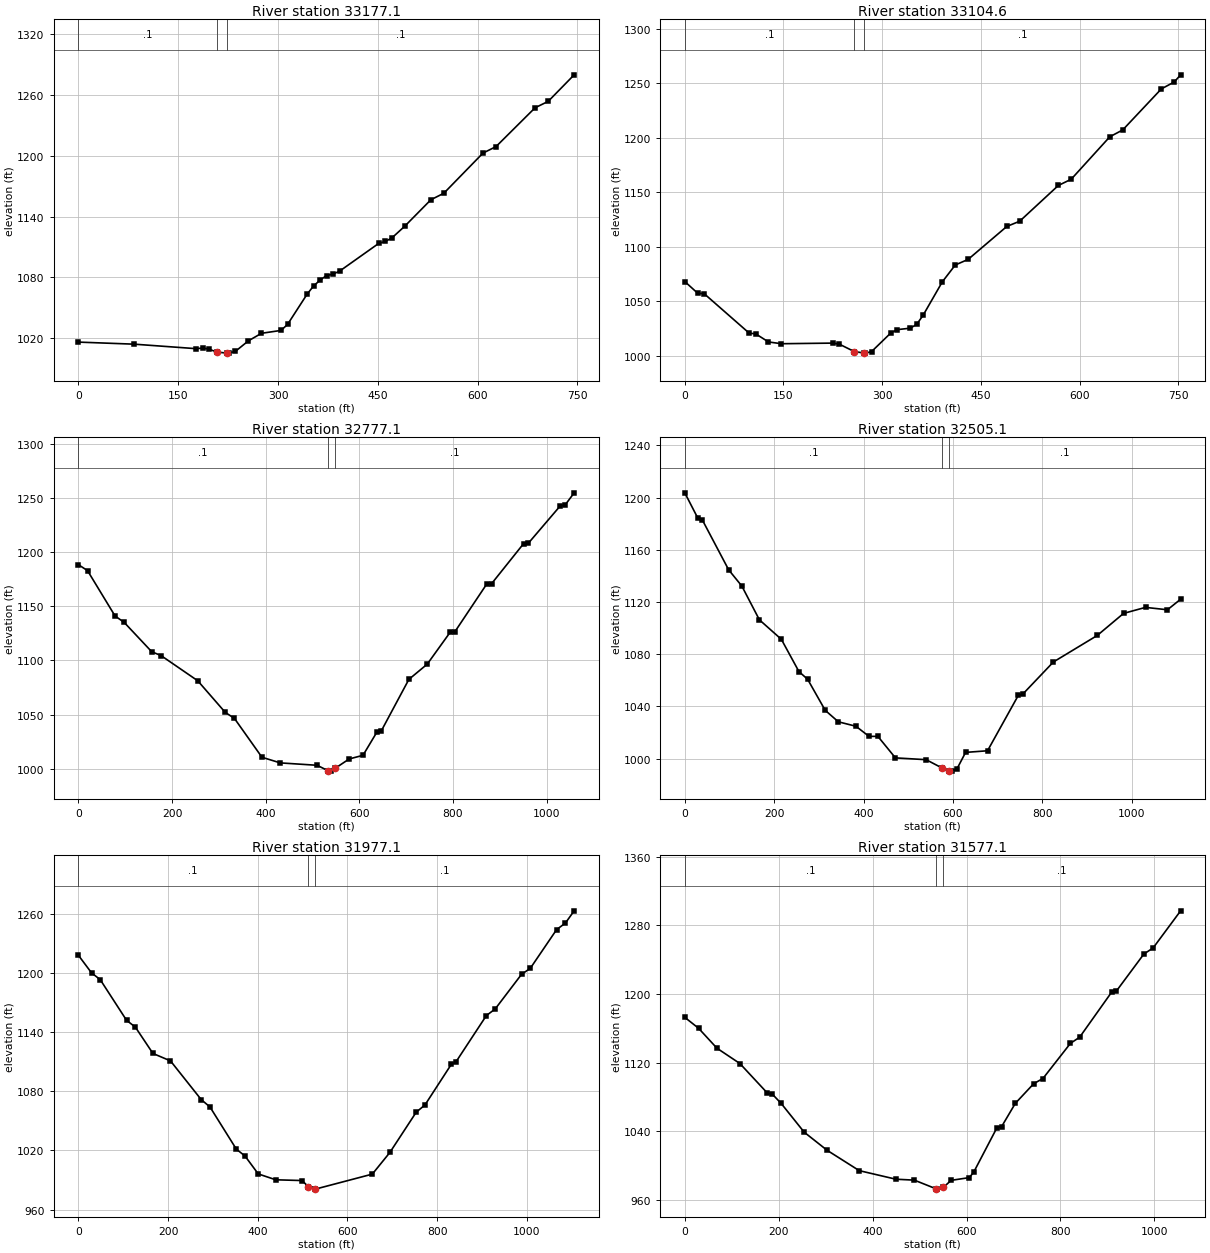
Type RM Length L Ch R = 1 ,33177.1 ,73.9,72.5,71
XS GIS Cut Line= 3
     1715607.535       314527.05      1715452.67      314613.326
     1715434.094      315180.757
#Sta/Elev= 30
       0 1016.02      84 1013.97   177.3 1009.52   187.1 1010.19   196.8 1008.98
   208.1 1006.16   223.1 1005.19   226.2 1005.13     236 1006.89   255.6 1017.29
   275.2 1024.71   304.5 1027.54   314.3  1033.4   343.7 1063.28   353.5 1071.48
   363.3 1077.21     373 1081.73   382.8 1083.17   392.6 1086.09   451.4 1113.47
   461.1 1115.36   470.9 1118.71   490.5 1130.44   529.7 1156.53   549.2 1162.98
     608 1202.61   627.6 1209.02   686.3 1247.36   705.9 1253.62     745 1279.87
#Mann= 3 , 0 , 0
       0      .1       0   208.1    .045       0   223.1      .1       0
Bank Sta=208.1,223.1
XS Rating Curve= 0 ,0
Exp/Cntr=0.3,0.1

Type RM Length L Ch R = 1 ,33104.6 ,324.7,327.5,330.4
XS GIS Cut Line= 2
     1715370.463      314388.422     1715395.185      315141.662
#Sta/Elev= 30
       0 1067.92    19.6 1057.18    29.4 1056.78    97.9 1020.54   107.7 1019.92
   127.2 1012.47   146.8 1010.84   225.1 1011.41   234.9 1010.43   257.8 1003.59
   272.8 1002.31     274 1002.21   283.8 1003.57   313.2 1020.77     323 1023.78
   342.6  1025.1   352.4 1028.57   362.1 1036.86   391.5 1067.73   411.1  1083.1
   430.6 1088.22   489.4 1118.46     509 1123.27   567.7 1156.06   587.3  1161.8
     646 1200.78   665.6 1207.04   724.3  1244.7   743.9 1251.05   753.6 1257.62
#Mann= 3 , 0 , 0
       0      .1       0   257.8    .045       0   272.8      .1       0
Bank Sta=257.8,272.8
XS Rating Curve= 0 ,0
Exp/Cntr=0.3,0.1

Type RM Length L Ch R = 1 ,32777.1 ,268.6,272,275.5
XS GIS Cut Line= 2
      1715104.87      314150.001     1715007.599      315204.244
#Sta/Elev= 30
       0 1188.38    19.6 1182.84    78.4    1141      98 1135.03   156.8 1107.97
   176.4 1104.52   254.9 1081.25   313.7 1052.05   333.3  1046.5   392.1 1010.64
   431.3 1005.45   509.8 1003.25   533.2  998.25   539.2  997.86   548.2 1000.42
   578.4  1009.1   607.8 1012.44   637.2 1033.66     647 1035.05   705.8 1082.51
     745 1096.56     794 1126.01   803.8 1126.31   872.5 1170.79   882.3 1170.74
   950.9 1207.84   960.7 1208.01  1029.3 1242.72  1039.1 1243.22  1058.7 1254.61
#Mann= 3 , 0 , 0
       0      .1       0   533.2    .045       0   548.2      .1       0
Bank Sta=533.2,548.2
XS Rating Curve= 0 ,0
Exp/Cntr=0.3,0.1

Type RM Length L Ch R = 1 ,32505.1 ,528.1,528,527.9
XS GIS Cut Line= 2
     1714926.114      314113.396     1714670.818      315193.405
#Sta/Elev= 30
       0 1203.61    29.5 1183.99    39.3 1182.81    98.2 1144.64   127.7  1132.2
     167 1106.34   216.1 1091.44   255.4 1066.76     275 1060.78   314.3 1037.04
   343.7 1028.25     383 1024.85   412.5 1017.07   432.1 1017.13   471.4 1000.63
   540.2  999.24   575.7  992.91   590.7   990.6   599.1  990.48   608.9  992.02
   628.5 1004.83   677.6 1006.07   746.4 1048.44   756.2 1049.34     825 1074.06
   923.2 1094.38   982.1 1111.28  1031.2 1115.88  1080.3 1114.05  1109.8 1122.13
#Mann= 3 , 0 , 0
       0      .1       0   575.7    .045       0   590.7      .1       0
Bank Sta=575.7,590.7
XS Rating Curve= 0 ,0
Exp/Cntr=0.3,0.1

Type RM Length L Ch R = 1 ,31977.1 ,399.1,400,400.9
XS GIS Cut Line= 2
     1714432.582       313991.36     1714180.369      315067.937
#Sta/Elev= 30
       0 1218.11    29.4 1200.22    48.9 1193.26   107.6 1152.02   127.2 1145.12
   166.4 1118.41   205.5 1110.87     274 1071.63   293.6  1064.1   352.3 1021.38
   371.8  1014.3   401.2   996.2   440.3  990.24     499  989.47   512.5  983.41
   527.5   980.8   528.4  980.77   655.6     996   694.8    1018   753.5 1058.83
     773 1066.15   831.7 1107.34   841.5 1109.44     910 1156.89   929.6 1163.56
   988.3 1198.66  1007.9 1204.78  1066.6 1244.09  1086.2 1250.73  1105.7 1263.12
#Mann= 3 , 0 , 0
       0      .1       0   512.5    .045       0   527.5      .1       0
Bank Sta=512.5,527.5
XS Rating Curve= 0 ,0
Exp/Cntr=0.3,0.1

Type RM Length L Ch R = 1 ,31577.1 ,402.3,400,397.7
XS GIS Cut Line= 2
     1714065.363      313905.044     1713784.287      314922.795
#Sta/Elev= 30
       0 1172.74    29.3 1160.04    68.4 1136.78   117.3 1118.88     176  1084.3
   185.8 1083.49   205.3 1072.26   254.2 1038.79   303.1 1017.63   371.5   993.9
   449.7  983.89   488.8  982.83   535.4  972.64   537.7  972.34   550.4  974.25
     567  982.57   606.1   985.8   615.9  992.86   664.8 1044.14   674.6 1045.25
   703.9 1072.49     743 1095.38   762.6 1101.39   821.2 1142.44   840.8 1149.59
   909.2 1202.37     919 1203.42   977.6 1246.66   997.2  1253.7  1055.8 1297.03
#Mann= 3 , 0 , 0
       0      .1       0   535.4    .045       0   550.4      .1       0
Bank Sta=535.4,550.4
XS Rating Curve= 0 ,0
Exp/Cntr=0.3,0.1

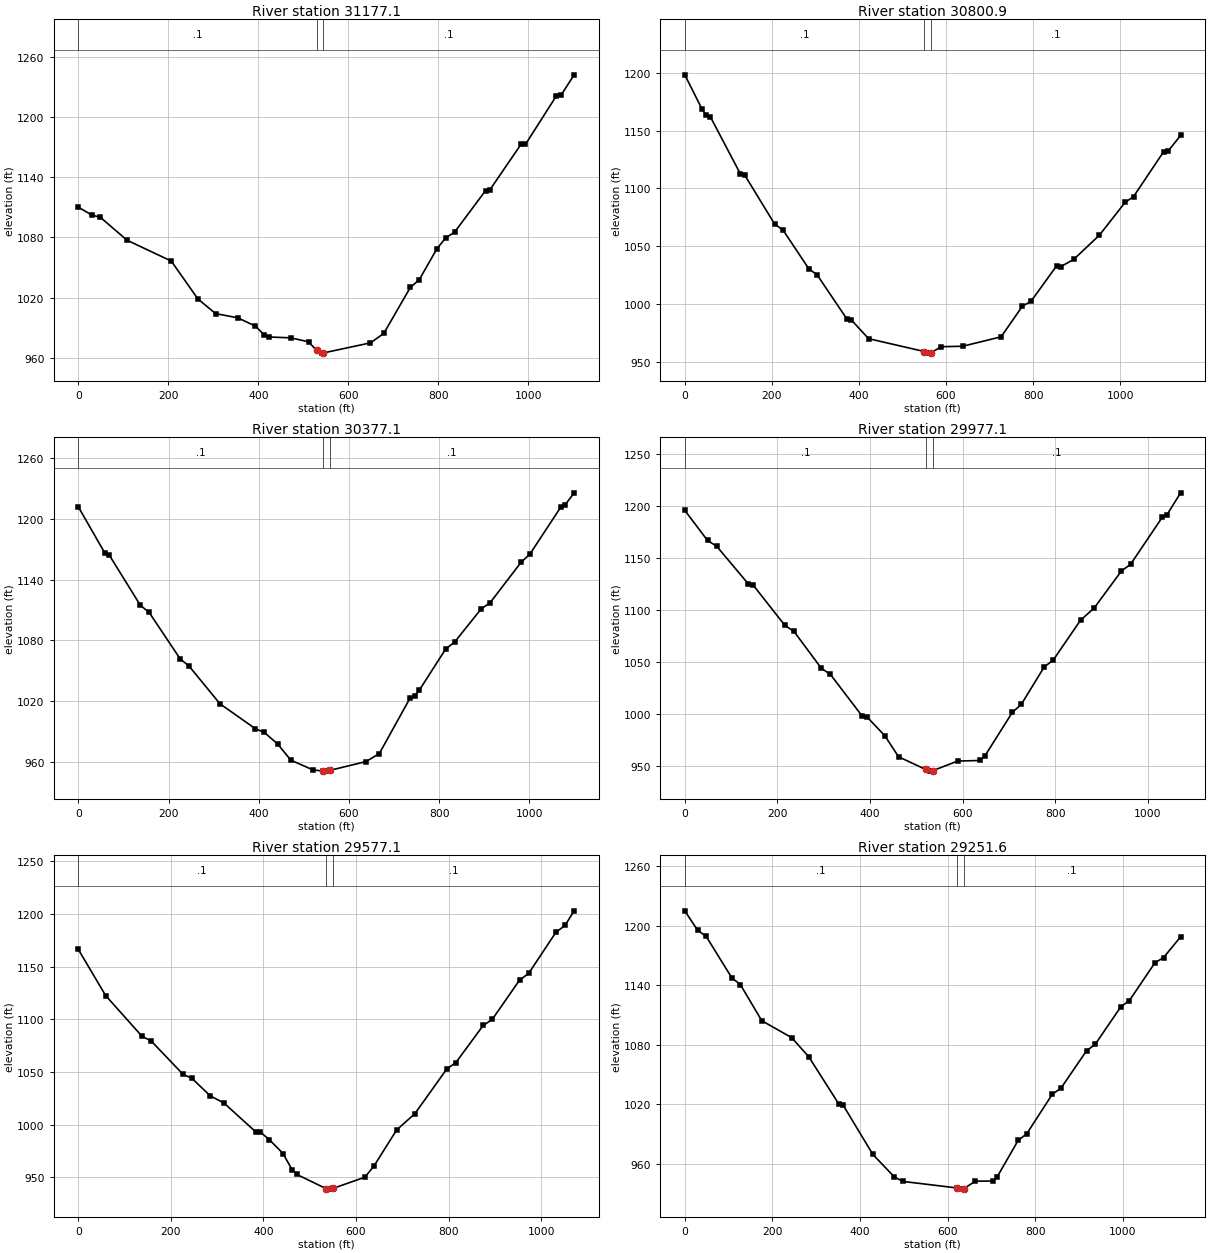
Type RM Length L Ch R = 1 ,31177.1 ,373.9,376.2,378.4
XS GIS Cut Line= 2
     1713638.591      313784.118     1713449.757      314869.906
#Sta/Elev= 30
       0 1110.06    29.5 1102.36    49.2  1099.9   108.2 1077.19   206.6 1056.41
   265.7 1018.77     305 1004.14   354.2  999.94   393.6  991.67   413.3  982.79
   423.1  980.83   472.3  979.98   511.7  976.02   529.7  967.39   541.2  964.76
   544.7  964.97   649.4  974.98     679   984.4     738  1030.2   757.7 1037.78
     797 1068.65   816.7 1079.58   836.4 1085.27   905.3 1126.66   915.1 1127.56
     984 1172.68   993.8 1172.52  1062.7 1220.99  1072.6 1221.36  1102.1 1241.84
#Mann= 3 , 0 , 0
       0      .1       0   529.7    .045       0   544.7      .1       0
Bank Sta=529.7,544.7
XS Rating Curve= 0 ,0
Exp/Cntr=0.3,0.1

Type RM Length L Ch R = 1 ,30800.9 ,420.1,423.8,427.6
XS GIS Cut Line= 2
      1713322.84      313743.257     1713015.469      314839.709
#Sta/Elev= 30
       0 1198.34    39.3 1168.85    49.1 1163.21    58.9 1161.86   127.6 1112.68
   137.4 1111.72   206.2 1069.29   225.8  1063.9   284.7 1030.62   304.3 1025.05
     373  986.66   382.8   986.1   422.1  970.06   550.4   958.9   559.5  957.54
   565.4  957.89     589   963.1   638.1  963.48   726.4  971.65   775.5  998.23
   795.1 1002.36     854 1033.13   863.9 1032.47   893.3 1038.67   952.2 1059.61
  1011.1 1087.94  1030.7 1093.04  1099.4 1131.69  1109.3 1132.05  1138.7  1145.9
#Mann= 3 , 0 , 0
       0      .1       0   550.4    .045       0   565.4      .1       0
Bank Sta=550.4,565.4
XS Rating Curve= 0 ,0
Exp/Cntr=0.3,0.1

Type RM Length L Ch R = 1 ,30377.1 ,403.3,400,396.7
XS GIS Cut Line= 2
      1713013.35      313636.521     1712566.048      314640.525
#Sta/Elev= 30
       0 1211.96    58.9 1166.17    68.7 1164.16   137.4 1114.65     157 1107.54
   225.7 1061.63   245.3 1054.52     314 1017.15   392.6  992.47   412.2  988.83
   441.6  977.54   471.1   961.4   520.1  951.79     543  950.58   549.6  950.56
     558  951.37   637.9  960.03   667.3  967.98     736 1023.37   745.8 1024.93
   755.7  1030.5   814.5 1071.51   834.2 1078.25     893 1111.09   912.7 1117.08
   981.4 1157.14    1001 1165.22  1069.7 1211.88  1079.5 1214.23  1099.1 1225.86
#Mann= 3 , 0 , 0
       0      .1       0     543    .045       0     558      .1       0
Bank Sta=543,558
XS Rating Curve= 0 ,0
Exp/Cntr=0.3,0.1

Type RM Length L Ch R = 1 ,29977.1 ,399.6,400,400.4
XS GIS Cut Line= 2
     1712605.846      313451.118     1712299.413      314476.908
#Sta/Elev= 30
       0 1195.64    49.1 1166.66    68.8 1161.14   137.5 1124.71   147.3 1123.93
   216.1 1084.96   235.7  1079.2   294.7 1043.77   314.3 1037.87     383  997.73
   392.9  997.15   432.2  978.65   461.6  958.57   520.4  946.36   530.4  944.78
   535.4  945.21   589.3  954.49   638.4  955.01   648.2  959.58   707.2 1001.25
   726.8 1009.13   775.9 1044.92   795.6 1051.66   854.5 1089.98     884 1101.71
   942.9  1137.4   962.5 1143.68  1031.3 1189.22  1041.1 1191.43  1070.6 1212.51
#Mann= 3 , 0 , 0
       0      .1       0   520.4    .045       0   535.4      .1       0
Bank Sta=520.4,535.4
XS Rating Curve= 0 ,0
Exp/Cntr=0.3,0.1

Type RM Length L Ch R = 1 ,29577.1 ,325.6,325.5,325.4
XS GIS Cut Line= 2
     1712241.262       313344.92      1711911.04      314364.108
#Sta/Elev= 30
       0 1166.28      59 1122.55   137.6 1083.89   157.3  1079.5   226.1 1047.85
   245.7 1043.91     285 1027.38   314.5 1020.66   383.3  993.24   393.2  993.05
   412.8  985.79   442.3  972.69     462  957.21   471.8   952.9   535.1  939.44
   540.6   938.9   550.1  939.55   619.2  950.22   638.9  960.89     688  995.13
   727.3 1010.53   796.1 1052.84   815.8 1058.96   874.8 1094.14   894.4 1099.91
   953.4 1137.17   973.1 1143.58    1032 1182.56  1051.7 1189.08  1071.4 1202.92
#Mann= 3 , 0 , 0
       0      .1       0   535.1    .045       0   550.1      .1       0
Bank Sta=535.1,550.1
XS Rating Curve= 0 ,0
Exp/Cntr=0.3,0.1

Type RM Length L Ch R = 1 ,29251.6 ,481.9,474.5,467.1
XS GIS Cut Line= 2
     1711950.216      313198.627     1711609.434      314278.324
#Sta/Elev= 30
       0 1214.98    29.3 1195.36    48.8 1189.26   107.4 1147.47   126.9 1140.69
   175.7 1104.31     244 1087.23     283 1067.98   351.4 1020.57   361.1 1019.53
   429.5  969.51   478.3  946.99   497.8  942.37   621.8  935.78   634.4   934.6
   636.8  935.04   663.7  942.61   702.7  942.74   712.5  946.33   761.3  983.75
   780.8  990.34   839.4  1030.3   858.9 1036.28   917.5 1074.06     937 1080.37
   995.6 1118.29  1015.1 1124.52  1073.6 1162.69  1093.2 1167.86  1132.2 1188.83
#Mann= 3 , 0 , 0
       0      .1       0   621.8    .045       0   636.8      .1       0
Bank Sta=621.8,636.8
XS Rating Curve= 0 ,0
Exp/Cntr=0.3,0.1

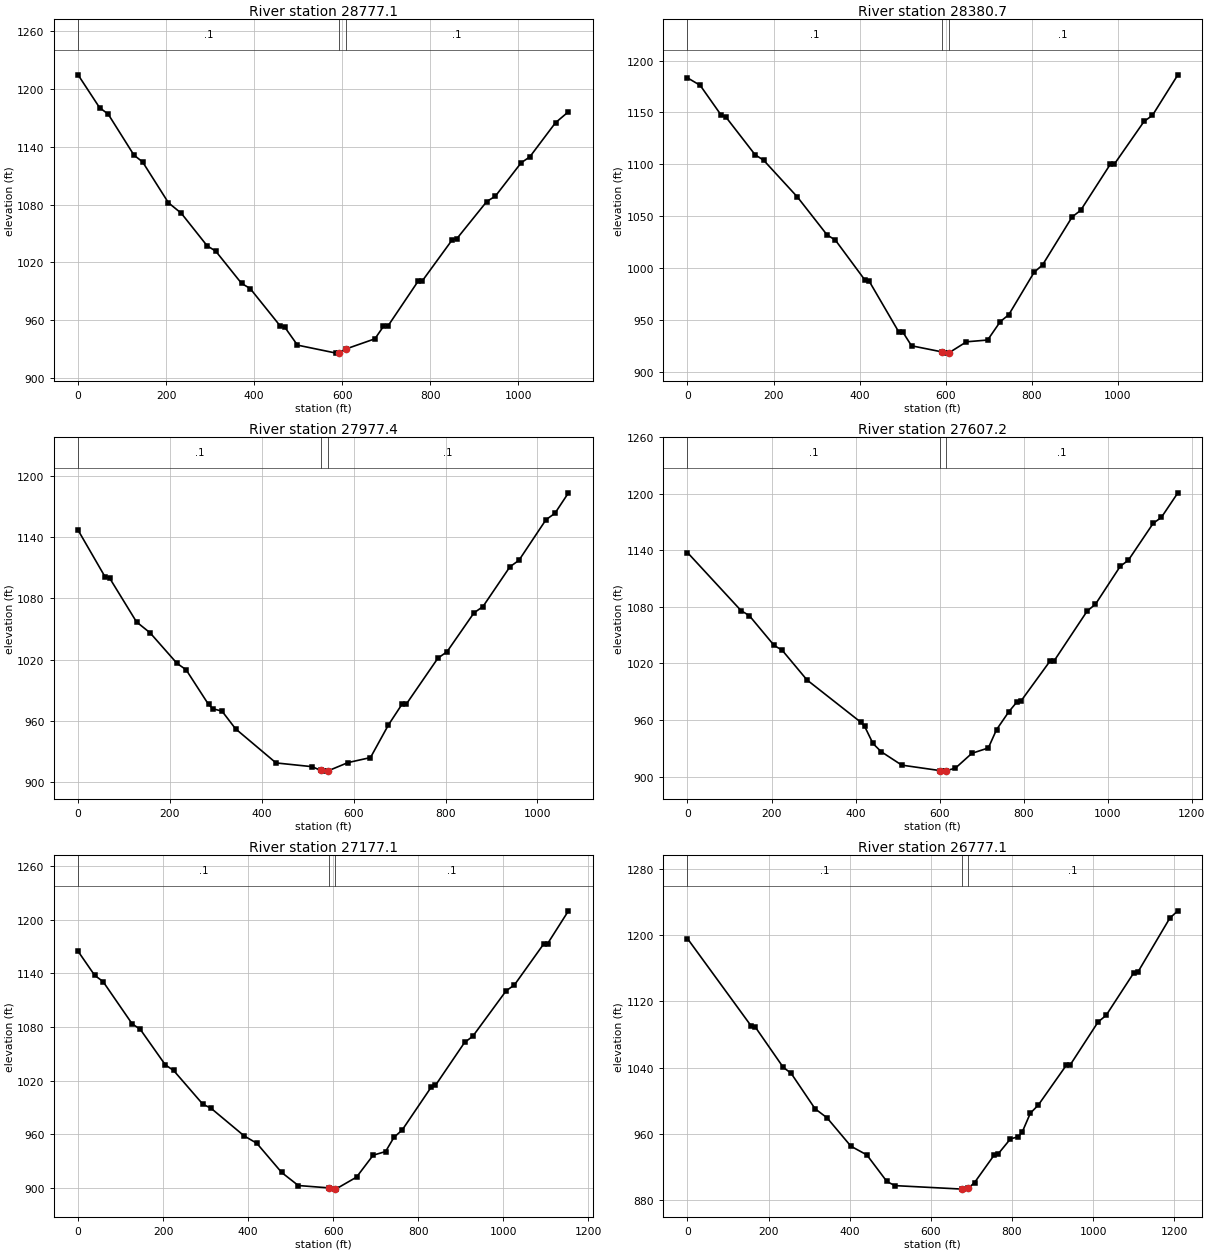
Type RM Length L Ch R = 1 ,28777.1 ,400,396.4,392.7
XS GIS Cut Line= 2
     1711290.516      313124.244     1711314.926      314238.017
#Sta/Elev= 30
       0 1214.87    48.9 1180.71    68.4 1174.03     127 1131.36   146.6 1124.29
   205.2 1081.88   234.5 1070.91   293.2 1037.07   312.7 1031.52   371.4  997.98
   390.9  992.65   459.3  953.66   469.1  952.73   498.4  933.78   586.3  925.45
   592.9  925.83   607.9  929.68   674.3  940.33   693.8  953.32   703.6  953.42
     772  999.96   781.8 1000.46   850.2 1043.46     860 1044.24   928.4 1083.12
   947.9 1088.65  1006.6 1123.44  1026.1 1129.51  1084.7 1165.15    1114 1176.48
#Mann= 3 , 0 , 0
       0      .1       0   592.9    .045       0   607.9      .1       0
Bank Sta=592.9,607.9
XS Rating Curve= 0 ,0
Exp/Cntr=0.3,0.1

Type RM Length L Ch R = 1 ,28380.7 ,402.3,403.4,404.4
XS GIS Cut Line= 2
     1710798.123      313148.325     1711006.894      314268.515
#Sta/Elev= 30
       0 1183.41    29.5 1176.19    78.6 1147.27    88.4 1146.09   157.2 1109.23
   176.8 1104.07   255.4 1068.56   324.2  1032.1   343.8 1026.91   412.6  988.32
   422.4  987.26   491.2  938.29     501  937.94   520.6  925.12   591.8  919.19
   599.2  918.04   606.8  918.15   648.3  928.96   697.4  930.66   726.9  948.42
   746.6  955.08   805.5  995.97   825.1 1003.09   893.9 1049.36   913.6 1055.68
   982.3 1099.97   992.1 1100.35  1060.9 1141.38  1080.5 1147.28  1139.5 1186.31
#Mann= 3 , 0 , 0
       0      .1       0   591.8    .045       0   606.8      .1       0
Bank Sta=591.8,606.8
XS Rating Curve= 0 ,0
Exp/Cntr=0.3,0.1

Type RM Length L Ch R = 1 ,27977.4 ,371.5,370.2,368.8
XS GIS Cut Line= 2
     1710432.668      313227.102     1710578.111      314284.726
#Sta/Elev= 30
       0 1146.69    58.8 1100.99    68.6 1099.89   127.3 1056.92   156.7 1046.32
   215.5 1016.36   235.1 1010.24     284  976.27   293.8  971.97   313.4  969.69
   342.8  952.45     431  919.07   509.3  915.41   528.8  911.67   538.7  911.05
   543.8  911.25   587.7  919.41   636.6   924.3   675.8  956.31   705.2  976.44
     715  976.84   783.5 1021.58   803.1 1027.73   861.9  1065.8   881.5 1071.99
   940.2 1110.87   959.8 1117.18  1018.6 1156.85  1038.2 1163.18  1067.6 1183.17
#Mann= 3 , 0 , 0
       0      .1       0   528.8    .045       0   543.8      .1       0
Bank Sta=528.8,543.8
XS Rating Curve= 0 ,0
Exp/Cntr=0.3,0.1

Type RM Length L Ch R = 1 ,27607.2 ,434.4,430.1,425.8
XS GIS Cut Line= 2
     1710025.083      313208.016     1710254.773      314352.332
#Sta/Elev= 30
       0 1137.61   127.5 1076.02   147.1  1070.7     206 1039.19   225.6 1033.86
   284.4 1002.46   411.9   957.8   421.7  953.14   441.4  935.05     461  926.32
     510  912.07   601.1  906.26   608.1   905.7   616.1  906.25   637.5   908.8
   676.8  924.58     716  930.29   735.6  949.74     765  968.84   784.6  979.39
   794.4  980.51   863.1 1022.62   872.9 1022.89   951.4 1075.65     971 1082.78
  1029.8 1122.93  1049.4 1129.56  1108.3 1168.58  1127.9 1174.95  1167.1 1200.97
#Mann= 3 , 0 , 0
       0      .1       0   601.1    .045       0   616.1      .1       0
Bank Sta=601.1,616.1
XS Rating Curve= 0 ,0
Exp/Cntr=0.3,0.1

Type RM Length L Ch R = 1 ,27177.1 ,399.2,400,400.8
XS GIS Cut Line= 2
     1709533.519      313423.075      1709965.02      314492.892
#Sta/Elev= 30
       0 1164.93    39.1 1137.92    58.7 1130.99   127.1 1083.63   146.6 1077.21
   205.3 1037.55   224.8 1031.25   293.3  993.53   312.8  988.89     391   957.8
   420.4  949.66     479  916.87   518.1  902.26   589.8  899.62   604.8  898.26
   606.1  898.22     655  911.67   694.1  936.23   723.4  940.37     743   956.2
   762.5  964.54     831 1012.79   840.7 1014.56   909.2 1062.65   928.7  1069.7
  1006.9 1120.53  1026.5 1127.18  1094.9 1172.81  1104.7  1173.6  1153.6 1210.26
#Mann= 3 , 0 , 0
       0      .1       0   589.8    .045       0   604.8      .1       0
Bank Sta=589.8,604.8
XS Rating Curve= 0 ,0
Exp/Cntr=0.3,0.1

Type RM Length L Ch R = 1 ,26777.1 ,558.6,561.1,563.6
XS GIS Cut Line= 2
     1709194.965      313531.913     1709608.802      314667.944
#Sta/Elev= 30
       0    1196   157.3 1090.16   167.1  1089.1   235.9 1040.46   255.6 1033.04
   314.6  990.19     344   979.3     403   944.9   442.3  934.37   491.5  902.31
   511.2  897.26   677.3  893.02   678.2     893   692.3  894.05   707.7  900.86
   756.9   934.7   766.7  936.02   796.2  953.71   815.9  956.38   825.7  962.45
   845.4  984.87     865   994.7   933.8 1042.68   943.7 1043.29  1012.5 1095.25
  1032.1 1103.11  1100.9 1154.97  1110.8 1155.75  1189.4 1220.91  1209.1 1229.59
#Mann= 3 , 0 , 0
       0      .1       0   677.3    .045       0   692.3      .1       0
Bank Sta=677.3,692.3
XS Rating Curve= 0 ,0
Exp/Cntr=0.3,0.1

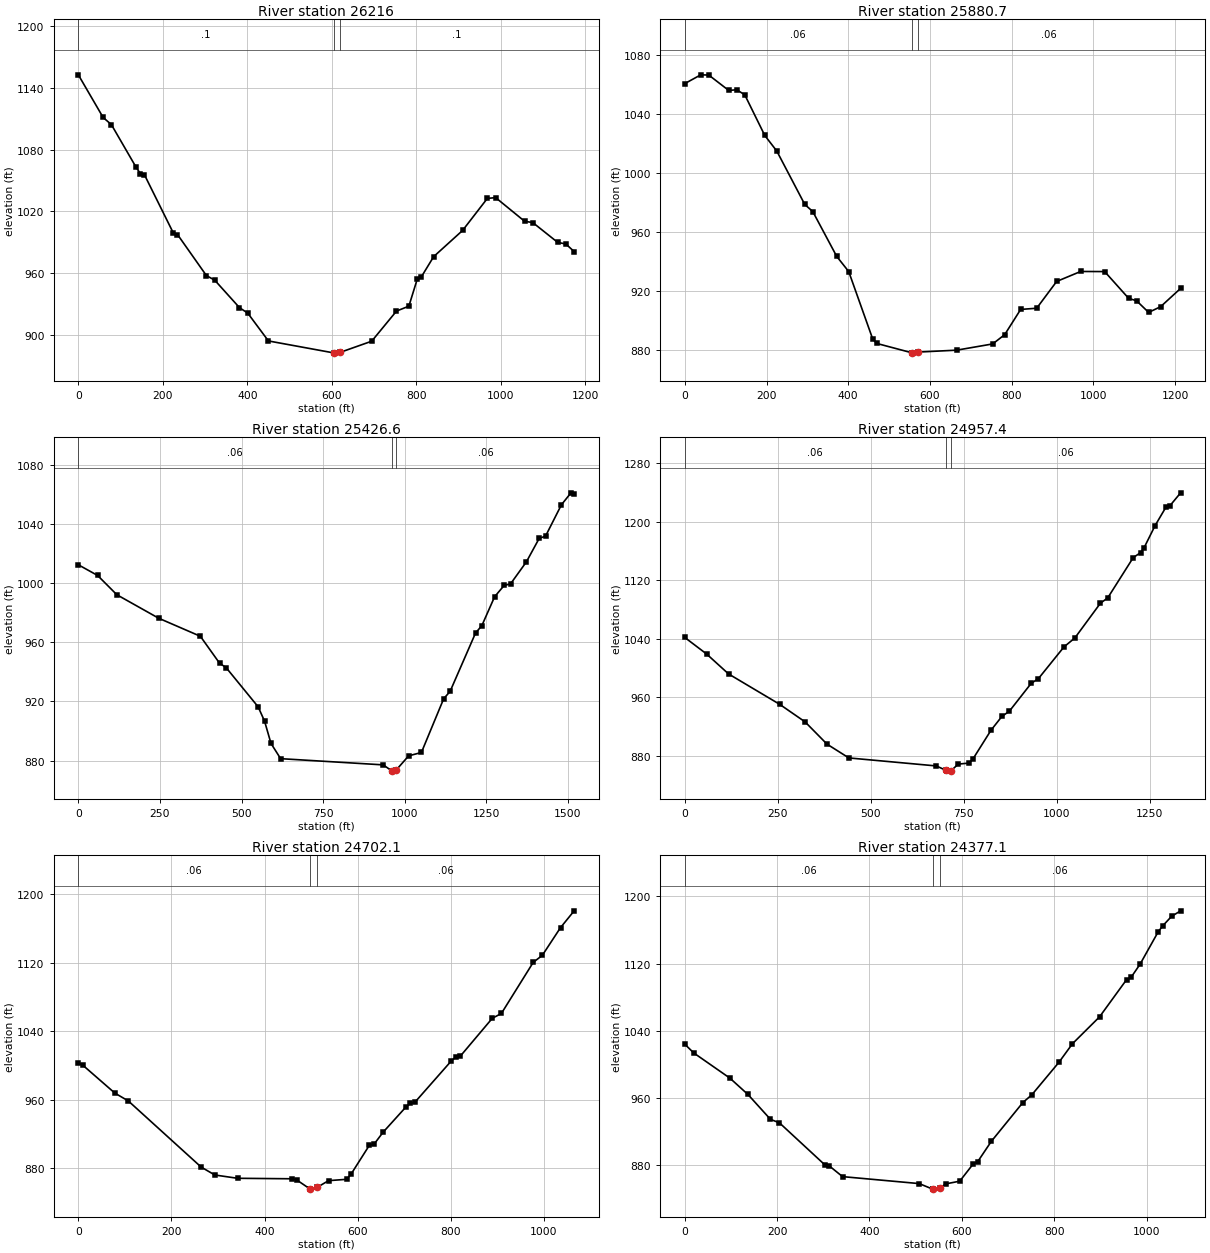
Type RM Length L Ch R = 1 ,26216   ,339.1,335.3,331.4
XS GIS Cut Line= 2
     1708790.368      313745.862     1709068.148      314886.621
#Sta/Elev= 30
       0 1152.35    58.7 1111.09    78.3 1104.11     137 1062.67   146.8 1056.78
   156.6 1055.52     225  999.13   234.8  997.69   303.3  957.92   322.9  953.51
   381.6  926.88   401.2  921.56   450.1  894.63   605.1  883.02   606.6  882.83
   620.1  883.59   694.7  894.38   753.4  923.56   782.7  928.31   802.3  954.19
   812.1  956.58   841.4  976.27   909.9 1001.63   968.6  1032.7   988.2 1033.42
  1056.7 1010.54  1076.2 1009.25    1135  990.11  1154.5  988.52  1174.1  981.15
#Mann= 3 , 0 , 0
       0      .1       0   605.1    .045       0   620.1      .1       0
Bank Sta=605.1,620.1
XS Rating Curve= 0 ,0
Exp/Cntr=0.3,0.1

Type RM Length L Ch R = 1 ,25880.7 ,457.8,454.2,450.5
XS GIS Cut Line= 2
       1708386.8      313829.389      1708869.03      314942.944
#Sta/Elev= 30
       0 1060.37    39.1 1066.31    58.7 1066.15   107.6 1055.72   127.2  1056.2
   146.8 1052.75   195.7 1025.24   225.1 1014.68   293.6  978.49   313.2  973.67
   371.9  943.23   401.2     933     460  887.22   469.7   884.3   555.3     878
   557.8  877.73   570.3  878.43   665.5  879.74   753.5  883.96   782.9  890.24
     822  907.35   861.2  908.15   910.1   926.3   968.8  933.06  1027.6  932.99
  1086.3  914.85  1105.8  913.18  1135.2  905.32  1164.6  909.21  1213.5   921.6
#Mann= 3 , 0 , 0
       0     .06       0   555.3    .045       0   570.3     .06       0
Bank Sta=555.3,570.3
XS Rating Curve= 0 ,0
Exp/Cntr=0.3,0.1

Type RM Length L Ch R = 1 ,25426.6 ,465.7,469.2,472.7
XS GIS Cut Line= 3
     1708272.998      313725.547      1708295.21      314610.715
     1708637.023      315144.448
#Sta/Elev= 30
       0 1012.43      59 1005.21   118.1  992.15     246   976.3   373.9  964.07
   432.9  945.81   452.6  942.93   550.9  916.35   570.6  906.65   590.3  891.59
   619.8  881.28   934.2  877.08   959.8  873.11   963.4  872.85   974.8  873.83
  1012.2   883.2  1051.2  885.47  1119.5  921.86    1139  926.75    1217  966.25
  1236.5  971.33  1275.5  990.82  1304.7  998.45  1324.2  999.48    1373 1014.46
    1412 1030.28  1431.5 1031.79  1480.2 1053.03  1509.5  1061.1  1519.2 1059.98
#Mann= 3 , 0 , 0
       0     .06       0   959.8    .045       0   974.8     .06       0
#XS Ineff= 2 , 0
          924.29  877.16
Permanent Ineff=
       F       F
Bank Sta=959.8,974.8
XS Rating Curve= 0 ,0
Exp/Cntr=0.3,0.1

Type RM Length L Ch R = 1 ,24957.4 ,255.7,255.3,254.8
XS GIS Cut Line= 2
     1707632.494      314238.363     1708172.289      315457.207
#Sta/Elev= 30
       0 1041.76    58.8 1019.11   117.6  992.01   254.8  950.59   323.4  926.52
   382.3  896.15   441.1   877.3   676.3  866.37   701.2  860.59   705.7  859.29
   716.2  860.03   735.1  868.87   764.5   870.3   774.3  875.58   823.3  915.18
   852.7  934.12   872.4  940.99   931.2   979.1   950.8  985.67  1019.4 1028.87
  1048.8 1041.19  1117.4 1088.56    1137  1095.8  1205.6 1150.83  1225.2 1157.53
    1235 1164.53  1264.4 1194.56  1293.8 1219.94  1303.6 1221.25    1333 1239.25
#Mann= 3 , 0 , 0
       0     .06       0   701.2    .045       0   716.2     .06       0
Bank Sta=701.2,716.2
XS Rating Curve= 0 ,0
Exp/Cntr=0.3,0.1

Type RM Length L Ch R = 1 ,24702.1 ,330.9,325,319.1
XS GIS Cut Line= 2
     1707465.314      314512.731     1707915.849       315477.52
#Sta/Elev= 30
       0 1003.16     9.8 1000.21    78.2  967.78   107.5  958.44   263.8  881.21
   293.1  871.97   341.9  868.12   459.1  867.54   468.9  866.24   497.6  855.58
   498.2  855.45   512.6  857.44   537.3  865.35   576.4  866.93   586.1  873.31
   625.2  906.86     635  907.93   654.5  921.97   703.4  951.36   713.1  955.78
   722.9  957.06     801 1005.29   810.8 1009.98   820.6 1011.03     889 1055.12
   908.5 1060.72   976.9 1120.48   996.4 1128.66  1035.5 1161.07  1064.8 1180.71
#Mann= 3 , 0 , 0
       0     .06       0   497.6    .045       0   512.6     .06       0
Bank Sta=497.6,512.6
XS Rating Curve= 0 ,0
Exp/Cntr=0.3,0.1

Type RM Length L Ch R = 1 ,24377.1 ,396.6,400,403.4
XS GIS Cut Line= 2
     1707069.005         314738.     1707757.957      315561.803
#Sta/Elev= 30
       0 1024.04    19.5 1013.59    97.6  983.69   136.7  964.25   185.5  934.63
     205  930.44   302.6   880.8   312.4  879.42   341.7  866.43   507.7  858.14
   536.8  851.57     537  851.55   551.8  853.03   566.2   857.9   595.5  861.01
   624.8  881.63   634.6   884.4   663.9  908.41   732.2  954.59   751.7  963.85
   810.3 1002.48   839.6  1024.6   898.2 1056.54   956.8 1100.86   966.5 1103.54
     986 1119.21  1025.1  1157.6  1034.9  1164.8  1054.4 1176.26  1073.9 1182.79
#Mann= 3 , 0 , 0
       0     .06       0   536.8    .045       0   551.8     .06       0
Bank Sta=536.8,551.8
XS Rating Curve= 0 ,0
Exp/Cntr=0.3,0.1

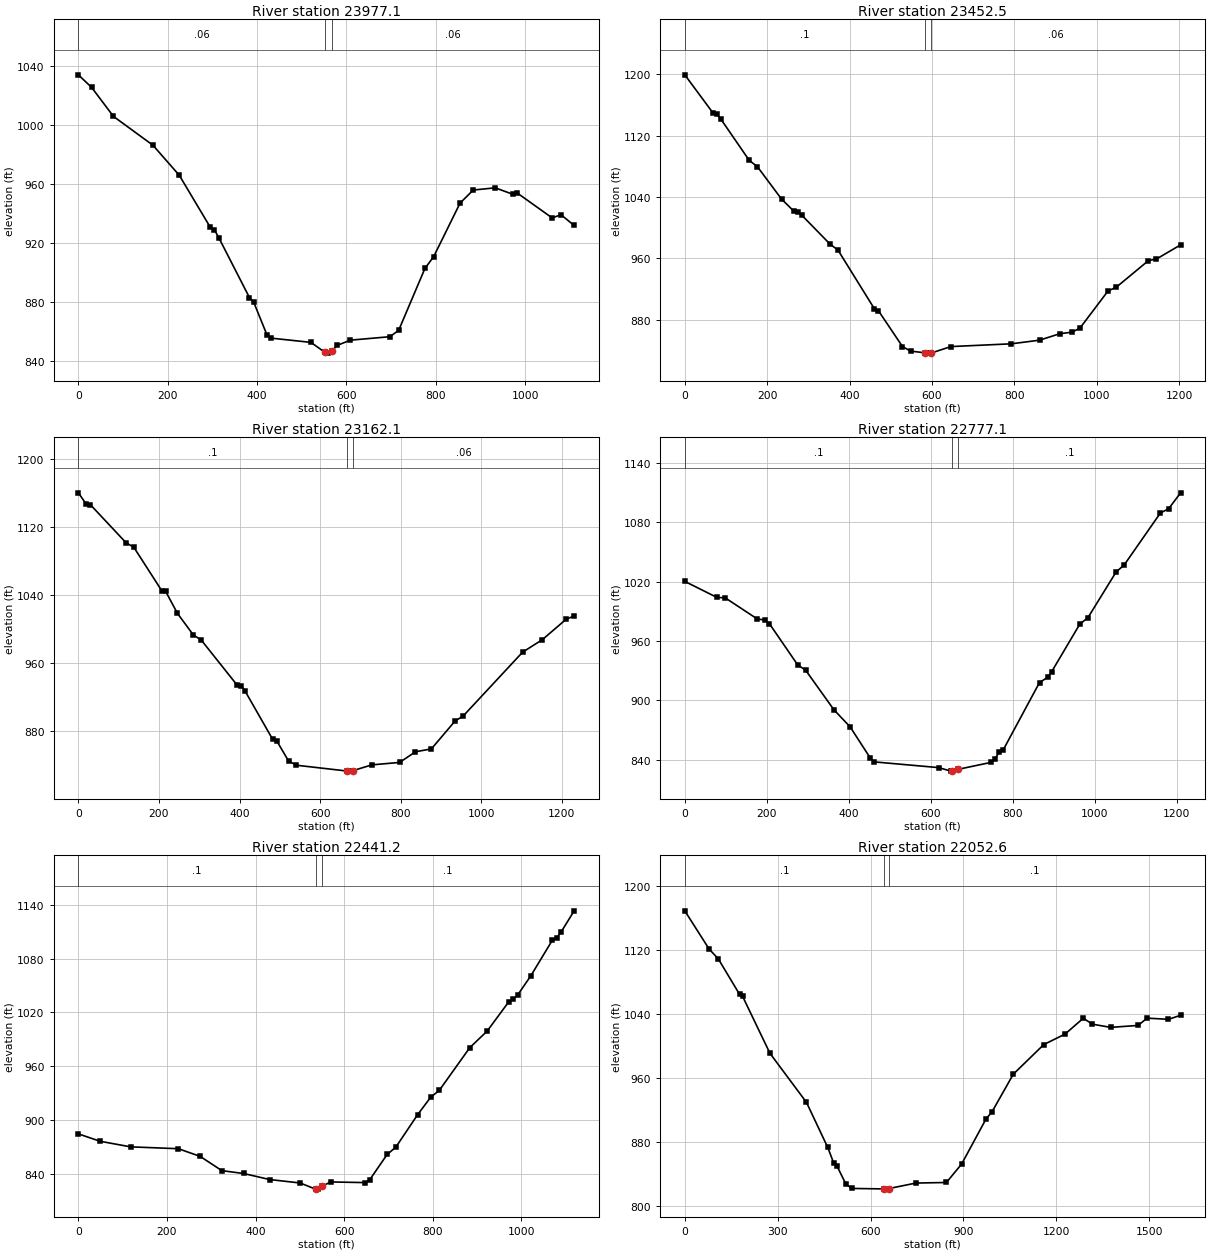
Type RM Length L Ch R = 1 ,23977.1 ,524.5,524.6,524.7
XS GIS Cut Line= 2
     1706825.958      314935.239     1707402.071      315884.006
#Sta/Elev= 30
       0 1033.83    29.5  1025.4    78.6 1005.66     167  986.11   225.9  965.78
   294.7  930.85   304.5  928.82   314.3  923.52   383.1  882.83   392.9  879.52
   422.4  857.45   432.2  855.33   520.6  852.48   552.1  845.73   559.9  845.19
   567.1   846.4   579.6  850.46     609  853.98   697.4  856.32   717.1  860.62
     776  902.65   795.6  910.64   854.6   946.9   884.1  955.74   933.2  957.23
   972.5  952.89   982.3  953.77  1060.9  936.82  1080.5  939.01    1110  931.72
#Mann= 3 , 0 , 0
       0     .06       0   552.1    .045       0   567.1     .06       0
Bank Sta=552.1,567.1
XS Rating Curve= 0 ,0
Exp/Cntr=0.3,0.1

Type RM Length L Ch R = 1 ,23452.5 ,287.2,290.4,293.5
XS GIS Cut Line= 2
     1706388.452      315089.038     1707016.918      316115.582
#Sta/Elev= 30
       0  1199.1    68.5 1149.38    78.3 1147.59    88.1 1140.94   156.6 1087.48
   176.1 1079.47   234.9 1037.11   264.2 1021.64     274 1020.81   283.8 1016.22
   352.3   978.6   371.9   970.6   459.9  894.44   469.7   891.9   528.4  844.95
     548  839.04   582.9  836.78   596.9  836.37   597.9  836.46   645.9   844.9
   792.6  848.51   861.2  853.25   910.1  861.64   939.4  863.66     959  868.82
  1027.5  917.48  1047.1  922.13  1125.4  956.94  1144.9  959.04  1203.6   977.5
#Mann= 3 , 0 , 0
       0      .1       0   582.9    .045       0   597.9     .06       0
Bank Sta=582.9,597.9
XS Rating Curve= 0 ,0
Exp/Cntr=0.3,0.1

Type RM Length L Ch R = 1 ,23162.1 ,388.6,385,381.5
XS GIS Cut Line= 2
     1706196.434      315187.904     1706739.501      316291.815
#Sta/Elev= 30
       0 1160.68    19.7 1147.34    29.5 1146.91   118.1 1102.06   137.8 1096.54
   206.7 1045.67   216.5 1044.79     246 1018.71   285.4  993.35   305.1  987.31
   393.7   934.5   403.5  933.82   413.4   927.6   482.3  870.38   492.1  868.82
   521.6     845   541.3  839.99   667.2  833.13   669.3  833.05   682.2  833.72
   728.3  840.43   797.2  843.29   836.6  855.83     876   859.2     935  892.16
   954.7  897.81  1102.3  973.07  1151.5  987.85  1210.6 1011.94  1230.3 1015.68
#Mann= 3 , 0 , 0
       0      .1       0   667.2    .045       0   682.2     .06       0
Bank Sta=667.2,682.2
XS Rating Curve= 0 ,0
Exp/Cntr=0.3,0.1

Type RM Length L Ch R = 1 ,22777.1 ,332.8,335.9,339
XS GIS Cut Line= 2
     1705817.765      315434.535     1706468.626      316454.169
#Sta/Elev= 30
       0  1020.2    78.7 1003.96    98.4 1003.65     177  982.19   196.7  981.15
   206.5  977.42   275.4  935.88     295  930.41   363.9  890.47   403.2  873.35
   452.4  841.84   462.2  837.86   619.6  832.07   649.1  828.53   652.2  828.64
   667.2  830.38   747.4  837.39   757.3   840.9   767.1  848.19   776.9     850
   865.4  918.05   885.1  923.25     895  928.94   963.8  977.12   983.5  983.52
  1052.3 1029.72    1072 1036.82  1160.5 1089.41  1180.2 1093.51  1209.7 1109.69
#Mann= 3 , 0 , 0
       0      .1       0   652.2    .045       0   667.2      .1       0
Bank Sta=652.2,667.2
XS Rating Curve= 0 ,0
Exp/Cntr=0.3,0.1

Type RM Length L Ch R = 1 ,22441.2 ,392,388.6,385.2
XS GIS Cut Line= 2
     1705652.927      315660.162     1706121.731      316676.367
#Sta/Elev= 30
       0  884.48    49.1  876.23   117.8     870   225.8  867.92   274.9  859.37
     324  843.44     373  840.28   431.9  833.53   500.7  829.69   535.3  822.85
   539.9  822.84   550.3  826.09   569.4  830.86   647.9  830.11   657.7  833.28
     697  861.53   716.6  869.64   765.7  905.82   795.2   925.3   814.8  933.05
   883.5  980.63   922.8  999.17   971.9 1032.05   981.7 1034.53   991.5 1039.36
    1021 1060.56    1070  1100.6  1079.9 1103.23  1089.7 1109.72  1119.1 1133.27
#Mann= 3 , 0 , 0
       0      .1       0   535.3    .045       0   550.3      .1       0
Bank Sta=535.3,550.3
XS Rating Curve= 0 ,0
Exp/Cntr=0.3,0.1

Type RM Length L Ch R = 1 ,22052.6 ,465.2,465,464.8
XS GIS Cut Line= 2
     1705178.408      315787.987      1706062.09      317123.654
#Sta/Elev= 30
       0 1169.34    78.6 1121.46   108.1 1109.24   176.9 1064.76   186.7 1062.26
   275.1  990.93     393  929.52   461.8  873.06   481.4  853.18   491.3     850
   520.7  826.94   540.4  821.78     644  821.17   648.5  820.92     659  821.62
   746.7  828.53     845  829.23   894.1   852.3   972.7  908.58   992.4   917.8
  1061.1  964.84  1159.4 1001.88  1228.2 1015.02  1287.1 1034.84  1316.6 1027.42
  1375.6 1023.42    1464 1025.87  1493.4 1034.99  1562.2  1033.5  1601.5 1038.57
#Mann= 3 , 0 , 0
       0      .1       0     644    .045       0     659      .1       0
Bank Sta=644,659
XS Rating Curve= 0 ,0
Exp/Cntr=0.3,0.1

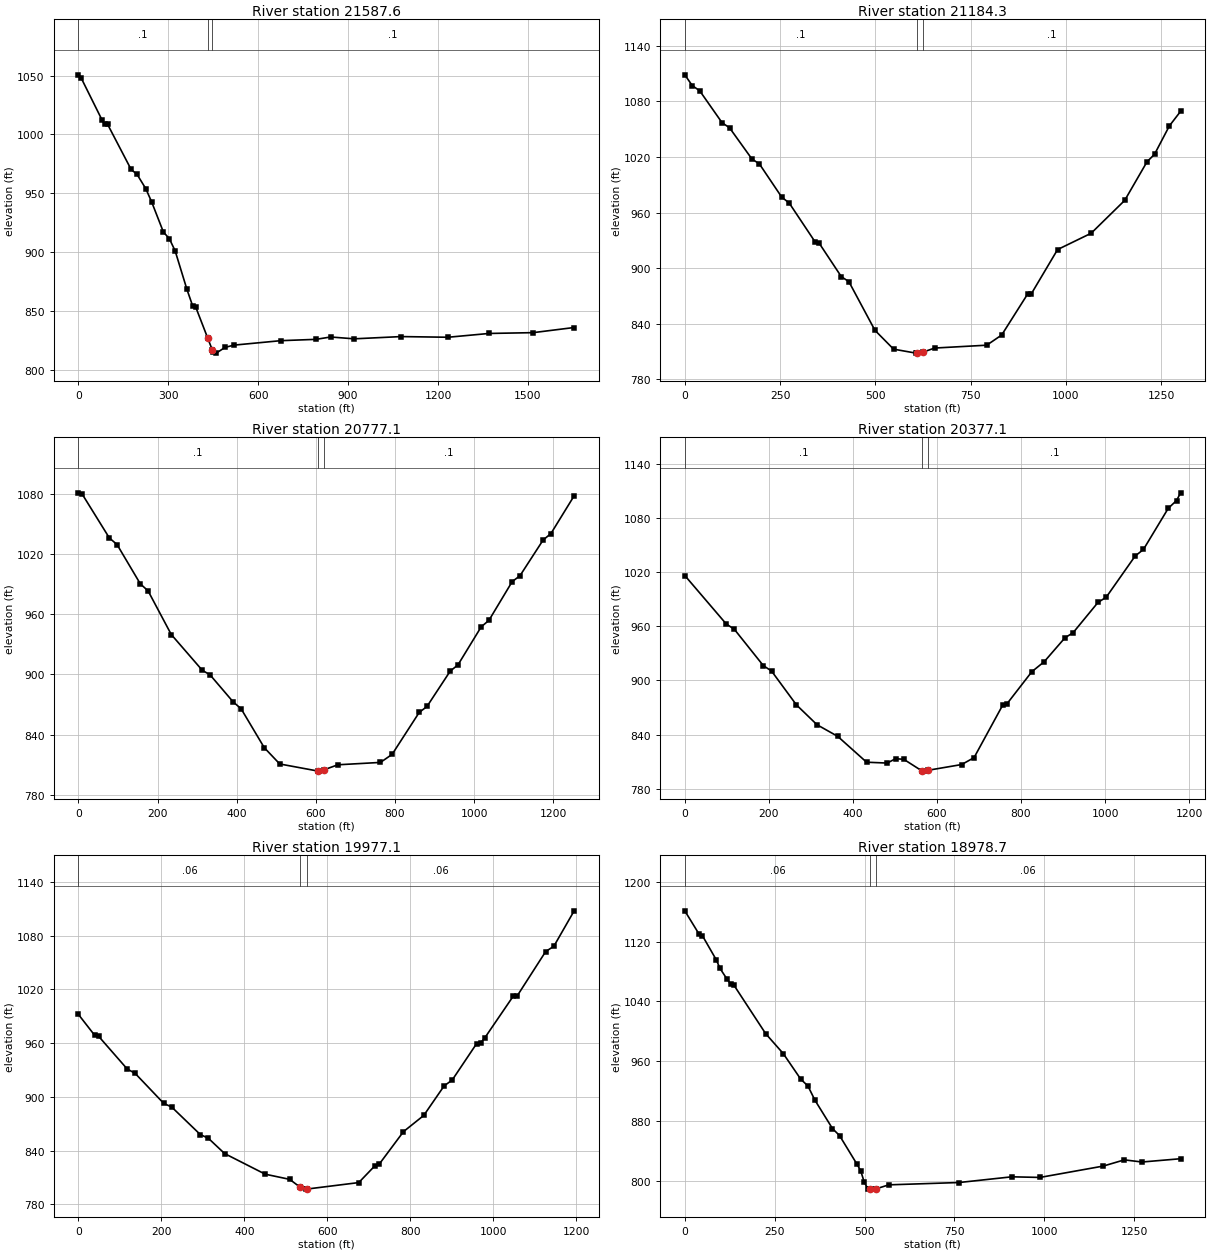
Type RM Length L Ch R = 1 ,21587.6 ,386.9,403.3,419.9
XS GIS Cut Line= 2
     1704876.017      316078.703     1705785.115      317460.943
#Sta/Elev= 30
       0 1050.71     9.8 1047.85    78.3 1012.71    88.1 1008.72    97.9 1008.49
   176.2  970.21   195.8  966.09   225.2  953.85   244.7   942.6   283.9  916.99
   303.5  911.47     323  901.03   362.2  868.38   381.8  853.96   391.6  853.28
   431.5  826.97   446.5  817.06   450.3  814.96   460.1  814.06   489.5  818.93
   518.8  820.85   675.5  824.65   792.9  825.78   841.9  827.78   920.2  826.22
  1076.8  828.13  1233.5  827.56  1370.5  830.79  1517.4  831.47  1654.4  835.85
#Mann= 3 , 0 , 0
       0      .1       0   431.5    .045       0   446.5      .1       0
Bank Sta=431.5,446.5
XS Rating Curve= 0 ,0
Exp/Cntr=0.3,0.1

Type RM Length L Ch R = 1 ,21184.3 ,408,407.2,406.4
XS GIS Cut Line= 2
     1704848.177      315961.351     1704640.541      317245.859
#Sta/Elev= 30
       0 1108.63    19.6    1097    39.1 1091.42    97.8 1056.96   117.4 1051.48
   176.1 1017.84   195.7  1012.5   254.4  976.63   273.9  970.33   342.4  928.07
   352.2  927.19   410.9  890.75   430.5   885.5     499   832.9   547.9  812.58
   606.6  808.29   608.9  808.29   623.9  809.17   655.5  813.77   792.4  816.85
   831.6  827.84   900.1  872.34   909.8  872.59   978.3  920.06  1066.4  937.66
  1154.4   973.1  1213.1 1014.85  1232.7 1022.88  1271.8  1053.6  1301.2 1069.27
#Mann= 3 , 0 , 0
       0      .1       0   608.9    .045       0   623.9      .1       0
Bank Sta=608.9,623.9
XS Rating Curve= 0 ,0
Exp/Cntr=0.3,0.1

Type RM Length L Ch R = 1 ,20777.1 ,396.5,400,403.4
XS GIS Cut Line= 2
     1704461.619       315883.59     1704319.471       317128.01
#Sta/Elev= 30
       0 1080.79     9.8 1079.46    78.3 1035.87    97.8 1029.25   156.6  990.11
   176.1  983.16   234.8  939.63   313.1  904.02   332.7  899.48   391.4  872.39
     411   865.8   469.7  826.92   508.8  810.68   605.4  803.62   606.7  803.56
   620.4  804.86   655.6  809.88   763.2  812.24   792.6  820.24   861.1  862.05
   880.7  867.95   939.4  903.18     959  909.41  1017.7  947.31  1037.2  953.76
    1096  992.37  1115.5  998.13  1174.2 1033.84  1193.8 1040.19  1252.5 1077.84
#Mann= 3 , 0 , 0
       0      .1       0   605.4    .045       0   620.4      .1       0
Bank Sta=605.4,620.4
XS Rating Curve= 0 ,0
Exp/Cntr=0.3,0.1

Type RM Length L Ch R = 1 ,20377.1 ,396.7,400,403.3
XS GIS Cut Line= 2
     1704168.164      315831.494     1703868.471      316972.691
#Sta/Elev= 30
       0 1016.31    98.3  962.78     118  956.66   186.8  916.52   206.5  910.42
   265.5  873.04   314.6  850.99   363.8  838.13   432.6  809.46   481.8  808.51
   501.4  813.34   521.1  812.68   564.4   799.8   570.3  799.58   579.4  800.56
   658.8  806.88   688.3  814.51   757.1  873.23   766.9   874.3   825.9  909.77
   855.4  920.86   904.6  947.27   924.2  953.03   983.2  986.47  1002.9   992.3
  1071.7 1037.91  1091.4 1045.16  1150.4 1090.72  1170.1 1099.38  1179.9 1107.92
#Mann= 3 , 0 , 0
       0      .1       0   564.4    .045       0   579.4      .1       0
#XS Ineff= 2 , 0
          510.19  812.63
Permanent Ineff=
       F       F
Bank Sta=564.4,579.4
XS Rating Curve= 0 ,0
Exp/Cntr=0.3,0.1

Type RM Length L Ch R = 1 ,19977.1 ,992.6,998.4,1004.2
XS GIS Cut Line= 2
     1703882.193      315720.432     1703410.764      316818.624
#Sta/Elev= 30
       0  992.18    39.2  968.87      49   967.6   117.6  931.25   137.1  926.18
   205.7  892.82   225.3  888.58   293.9  857.99   313.5  853.76   352.6  836.72
   450.6  813.68   509.4  807.94   535.1  799.01   548.6  797.02   550.1  797.05
   675.9  804.33   715.1  823.22   724.9  824.68   783.7  861.21   832.6   879.3
   881.6  912.24   901.2  918.86     960  959.48   969.8  960.44   979.6  965.84
  1048.2 1012.42    1058 1012.92  1126.5 1062.32  1146.1 1068.13  1195.1 1107.74
#Mann= 3 , 0 , 0
       0     .06       0   535.1    .045       0   550.1     .06       0
Bank Sta=535.1,550.1
XS Rating Curve= 0 ,0
Exp/Cntr=0.3,0.1

Type RM Length L Ch R = 1 ,18978.7 ,583.3,586.4,589.5
XS GIS Cut Line= 2
     1703147.658      315285.342     1702299.444      316372.924
#Sta/Elev= 30
       0 1161.24    39.1 1130.53    48.9 1128.04      88 1095.26    97.8  1084.2
   117.4 1069.87   127.2 1063.47     137 1061.44     225  996.75   273.9   970.1
   322.8  935.68   342.4  926.83   361.9  907.77   410.8   869.7   430.4  860.35
   479.3  821.72   489.1   813.5   498.9   798.3   508.7  789.34   516.2  788.79
   518.4  788.63   531.2  788.91   567.4  794.36     763  797.48   909.7  805.12
     988  804.29    1164   819.5  1222.7  827.82  1271.6  824.93  1379.2  829.34
#Mann= 3 , 0 , 0
       0     .06       0   516.2    .045       0   531.2     .06       0
Bank Sta=516.2,531.2
XS Rating Curve= 0 ,0
Exp/Cntr=0.3,0.1