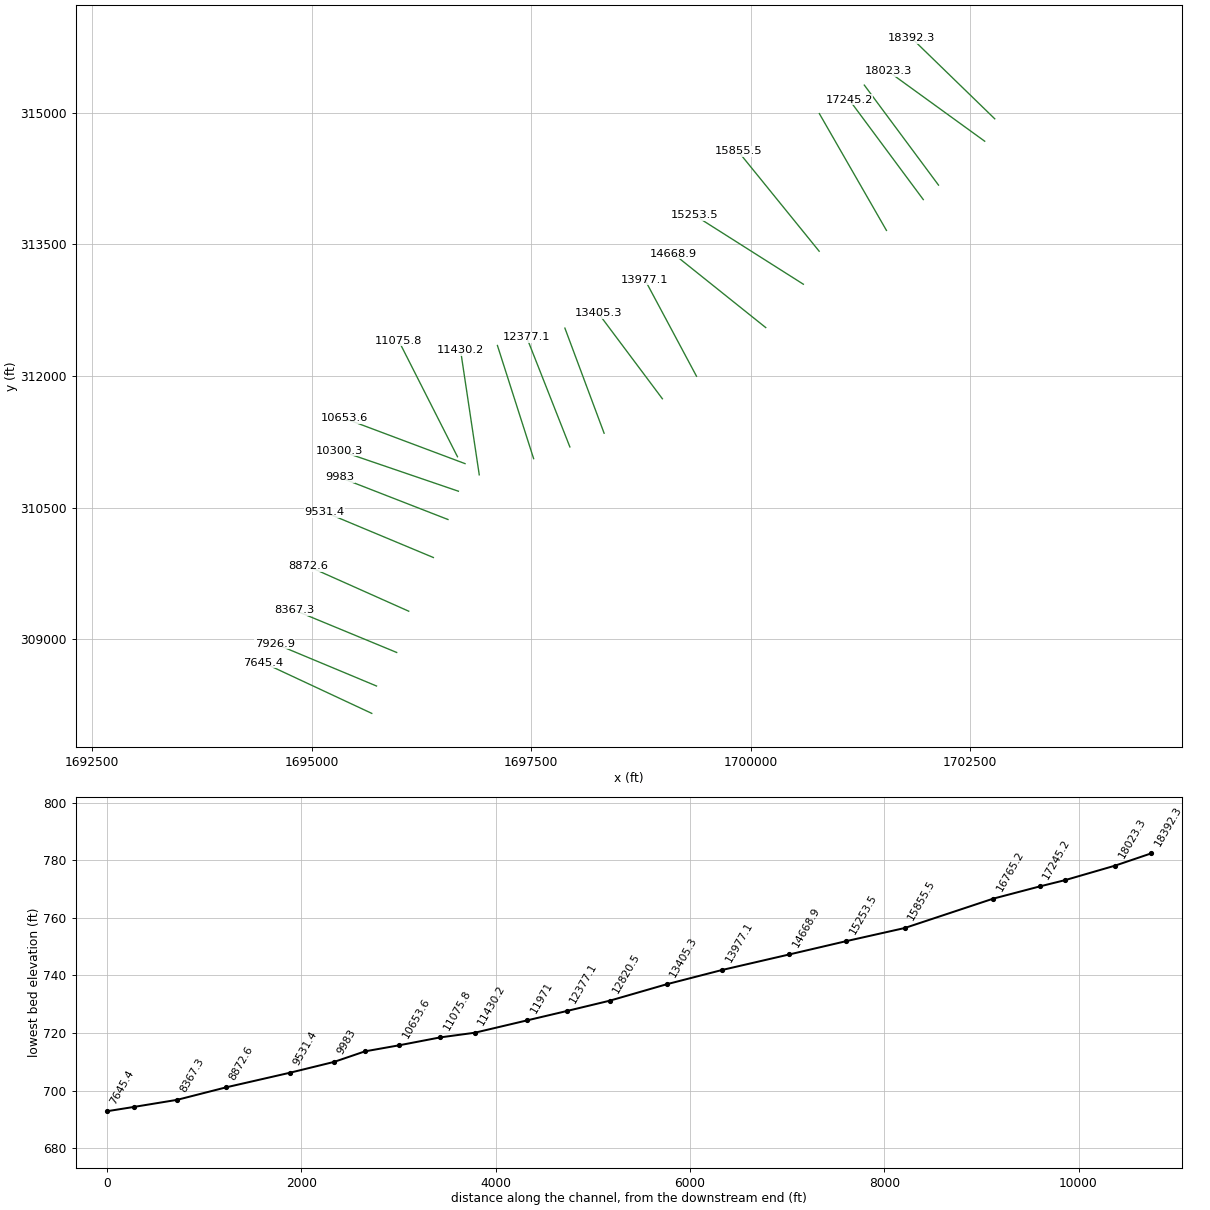
HEC-RAS study DINGESSRN.prj: DINGESSRN

--- DINGESSRN.g01 (geometry) --- (continued)

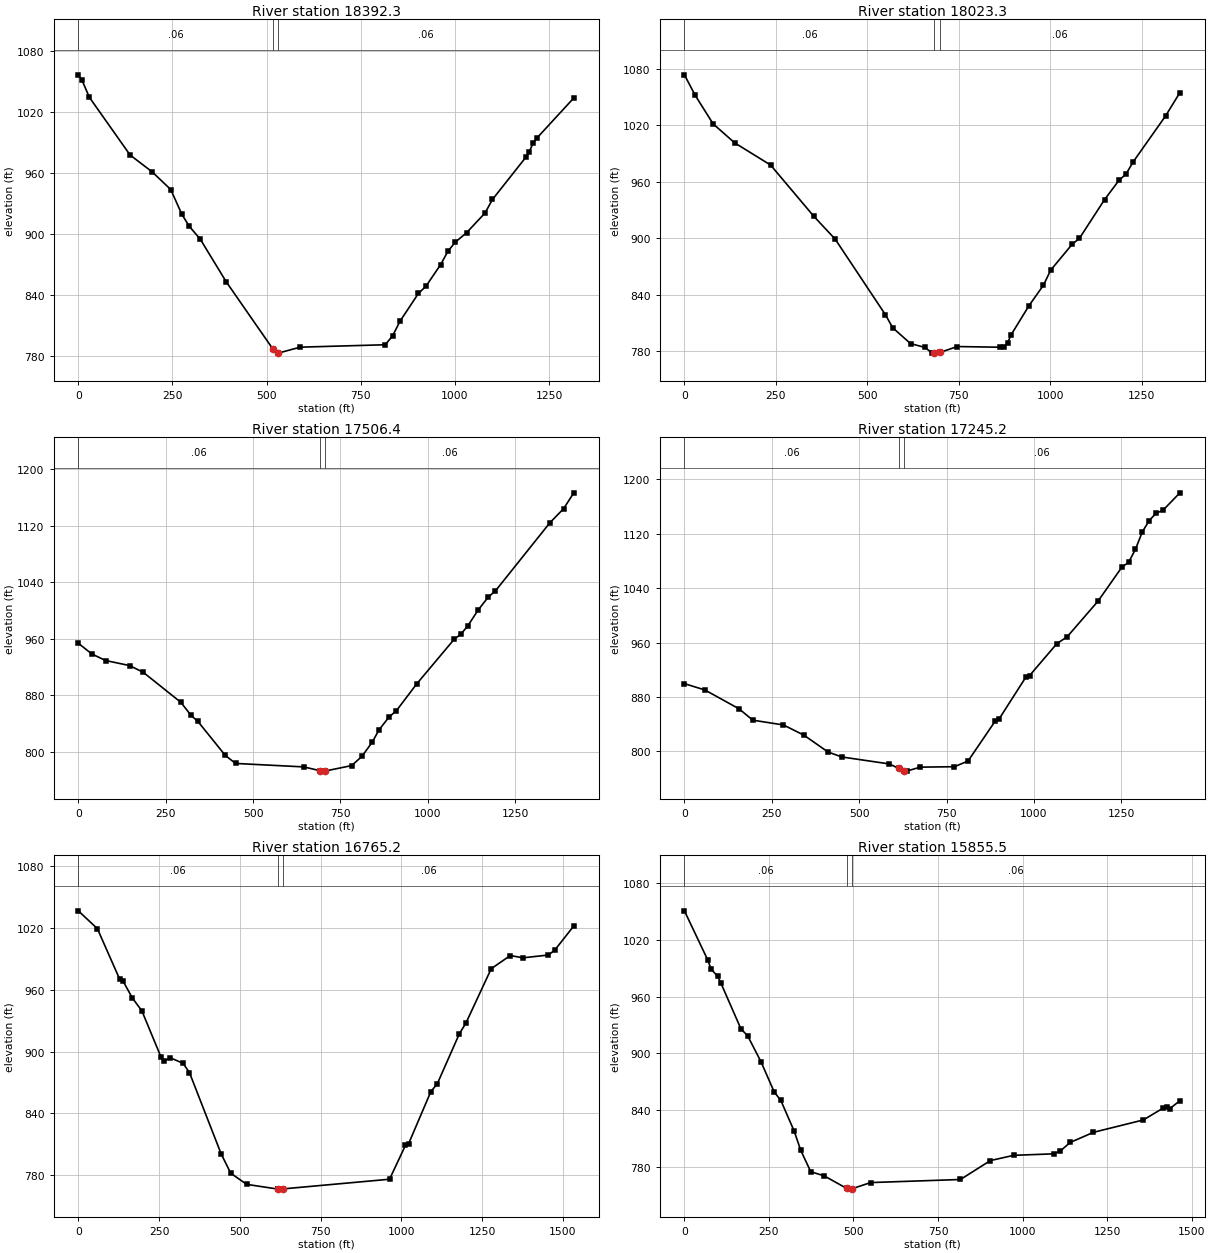
Type RM Length L Ch R = 1 ,18392.3 ,365.4,369,372.7
XS GIS Cut Line= 2
     1702778.851      314928.647     1701835.147      315845.005
#Sta/Elev= 30
       0 1056.22     9.8 1050.89    29.4 1034.06   137.4  977.35   196.3  960.66
   245.4  943.34   274.9  918.95   294.5  907.21   323.9  894.42   392.7  852.54
   515.7  786.89   530.1   782.4   530.7  782.42     589  788.26   814.8  790.64
   834.4  799.47     854  813.79   903.1  841.26   922.8  848.15     962  869.57
   981.6  882.85  1001.3  891.76  1030.7  900.86  1079.8   920.3  1099.4  933.57
  1187.8  974.98  1197.6  980.78  1207.4   989.2  1217.2  993.92  1315.4 1033.45
#Mann= 3 , 0 , 0
       0     .06       0   515.7    .045       0   530.7     .06       0
Bank Sta=515.7,530.7
XS Rating Curve= 0 ,0
Exp/Cntr=0.3,0.1

Type RM Length L Ch R = 1 ,18023.3 ,524.3,516.9,509.4
XS GIS Cut Line= 2
     1702664.389      314673.547     1701567.294      315467.843
#Sta/Elev= 30
       0 1073.83    29.4  1052.1    78.5 1021.72   137.4 1001.55   235.6  977.98
   353.3  923.73   412.2  899.21   549.6   818.9   569.3  805.13   618.3  788.25
   657.6  784.25   677.2  778.17   683.4   778.2   698.4   778.9   745.9  785.16
   863.7  784.44   873.5  784.99   883.3   789.1   893.2  797.74   942.2  828.76
   981.5  850.37  1001.1  866.27    1060  893.87  1079.6     900  1148.3  941.18
  1187.6  961.61  1207.2  968.47  1226.8  981.44  1315.2 1030.12  1354.4 1054.94
#Mann= 3 , 0 , 0
       0     .06       0   683.4    .045       0   698.4     .06       0
Bank Sta=683.4,698.4
XS Rating Curve= 0 ,0
Exp/Cntr=0.3,0.1

Type RM Length L Ch R = 1 ,17506.4 ,261.8,261.3,260.6
XS GIS Cut Line= 2
     1702138.321      314173.741     1701293.539      315312.271
#Sta/Elev= 30
       0   953.7    39.1  938.47    78.2  929.31   146.7   922.2   185.8  912.68
   293.3  870.32   322.6  851.82   342.2  843.28   420.4  795.41   449.8  783.97
   645.3  779.07   691.1  773.74     704  773.11   706.1  773.21   782.2  780.96
   811.5  793.98   840.8  813.91   860.4  831.35   889.7  849.99   909.3  857.91
     968   896.2  1075.5  959.38  1095.1  966.78  1114.6  978.39    1144 1000.63
  1173.3 1019.18  1192.8 1027.27  1349.3  1123.9  1388.4 1143.73  1417.7 1166.17
#Mann= 3 , 0 , 0
       0     .06       0   691.1    .045       0   706.1     .06       0
Bank Sta=691.1,706.1
XS Rating Curve= 0 ,0
Exp/Cntr=0.3,0.1

Type RM Length L Ch R = 1 ,17245.2 ,482,480,478.1
XS GIS Cut Line= 2
     1701965.163      314008.668     1701120.381      315147.198
#Sta/Elev= 30
       0  899.56    58.7  890.21   156.4  862.48   195.6  845.85   283.5  838.77
   342.2  823.69   410.6  799.14   449.8  791.79   586.6  781.47   613.5  774.84
   628.5  771.68   635.5  770.92   674.6  776.77   772.4  777.42   811.5  785.74
   889.7  844.82   899.5  846.87   977.7  909.71   987.5  911.36  1065.7  958.33
  1095.1   968.4  1183.1 1020.59  1251.5 1070.62    1271 1077.96  1290.6 1097.09
  1310.2 1122.69  1329.7 1139.07  1349.3 1150.09  1368.8 1154.14  1417.7 1180.05
#Mann= 3 , 0 , 0
       0     .06       0   613.5    .045       0   628.5     .06       0
Bank Sta=613.5,628.5
XS Rating Curve= 0 ,0
Exp/Cntr=0.3,0.1

Type RM Length L Ch R = 1 ,16765.2 ,906.4,909.7,912.9
XS GIS Cut Line= 2
     1701545.579      313657.631     1700781.528      314987.786
#Sta/Elev= 30
       0  1036.5      59  1019.2   127.8  970.38   137.7  968.83   167.2  952.01
   196.7  939.55   255.7  894.93   265.5  890.94   285.2  893.98   324.5   888.6
   344.2  879.56   442.5  800.59     472  782.06   521.2  771.28   618.5  766.68
   619.5  766.66   633.5  766.88   963.6  776.26  1012.8  809.14  1022.6  810.72
  1091.5  861.28  1111.2  868.69    1180  917.54  1199.6   927.4  1278.3  980.36
  1337.3  993.14  1376.6  990.94  1455.3  993.65    1475  998.38    1534 1021.83
#Mann= 3 , 0 , 0
       0     .06       0   618.5    .045       0   633.5     .06       0
Bank Sta=618.5,633.5
XS Rating Curve= 0 ,0
Exp/Cntr=0.3,0.1

Type RM Length L Ch R = 1 ,15855.5 ,594.3,602,609.7
XS GIS Cut Line= 2
     1700779.329      313420.702     1699856.221      314558.718
#Sta/Elev= 30
       0 1050.86    68.8  999.03    78.7   989.4    98.3  981.51   108.2  974.16
   167.2  925.96   186.8  918.76   226.2  891.42   265.5   859.3   285.2  850.25
   324.5  817.92   344.2  797.35   373.7  774.86     413  770.58   479.7  757.27
   491.7  756.47   494.7  756.77   550.7   763.4   816.3  766.66   904.8  786.67
   973.6  792.22  1091.6   793.8  1111.3   796.7  1140.8  805.82  1209.6  816.54
  1357.2  829.65  1416.2  842.29    1426  843.74  1435.8  841.66  1465.3  850.02
#Mann= 3 , 0 , 0
       0     .06       0   479.7    .045       0   494.7     .06       0
Bank Sta=479.7,494.7
XS Rating Curve= 0 ,0
Exp/Cntr=0.3,0.1

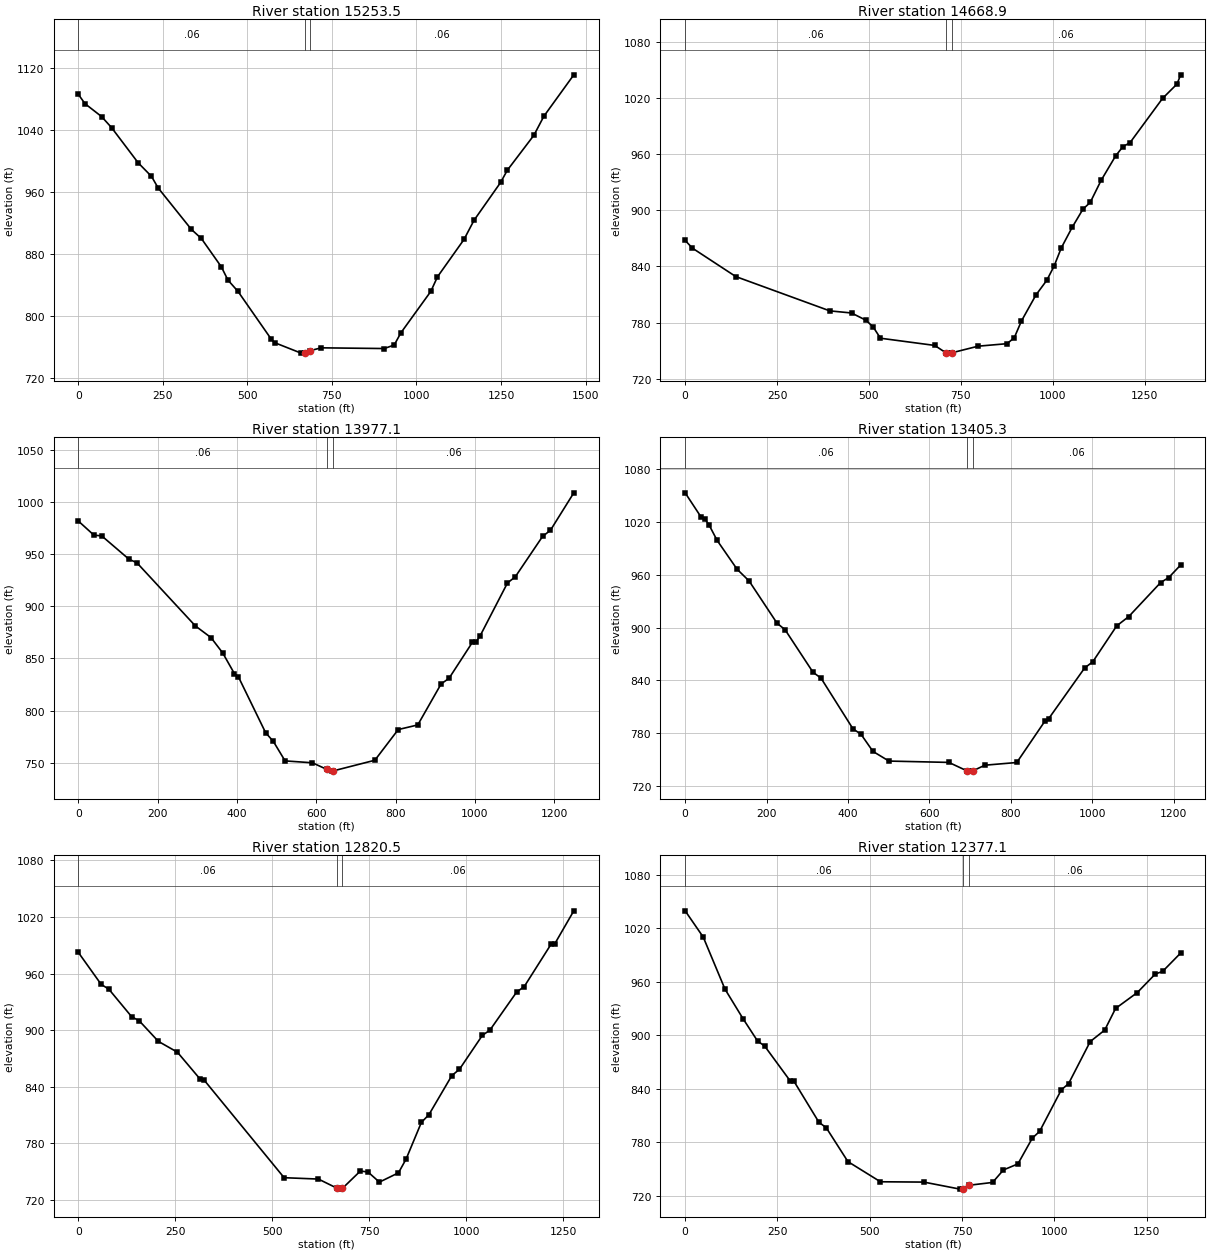
Type RM Length L Ch R = 1 ,15253.5 ,587.2,584.6,582
XS GIS Cut Line= 2
     1700599.343      313044.937     1699361.785      313829.443
#Sta/Elev= 30
       0 1085.91    19.7 1073.86    68.8  1057.2    98.3 1042.96     177  997.54
   216.4  980.01     236  965.16   334.4  911.55   363.9  899.85   422.9  863.32
   442.5  846.17     472  831.69   570.4  770.05   580.2  765.46   658.9  751.91
   669.1  752.06   684.1  754.91   717.9  758.75   904.7  757.83   934.2  762.39
   953.9  778.09  1042.4  831.55  1062.1  850.37  1140.7   898.7  1170.2  923.33
  1248.9  972.22  1268.6   987.9  1347.3  1033.1  1376.8 1057.64  1465.3 1111.08
#Mann= 3 , 0 , 0
       0     .06       0   669.1    .045       0   684.1     .06       0
Bank Sta=669.1,684.1
XS Rating Curve= 0 ,0
Exp/Cntr=0.3,0.1

Type RM Length L Ch R = 1 ,14668.9 ,701,691.8,682.6
XS GIS Cut Line= 2
       1700170.5      312551.534     1699117.728      313393.598
#Sta/Elev= 30
       0  867.71    19.7  859.48   137.8  829.09   393.6  792.44   452.6  790.19
     492  782.42   511.7  775.15   531.4  763.22     679  755.52   710.3  747.43
   718.3   747.3   725.3  747.62   797.1  754.72   875.8  757.39   895.5   763.8
   915.1  781.75   954.5  809.47     984  825.16  1003.7  840.21  1023.4  859.74
  1052.9  881.65  1082.4  901.18  1102.1  908.29  1131.6  931.78    1171  957.87
  1190.7  967.78  1210.4  972.16  1298.9 1019.45  1338.3 1034.84  1348.1 1044.63
#Mann= 3 , 0 , 0
       0     .06       0   710.3    .045       0   725.3     .06       0
Bank Sta=710.3,725.3
XS Rating Curve= 0 ,0
Exp/Cntr=0.3,0.1

Type RM Length L Ch R = 1 ,13977.1 ,568.1,571.8,575.4
XS GIS Cut Line= 2
     1699382.708      311996.655      1698793.82      313098.388
#Sta/Elev= 30
       0  981.65    39.4  968.08      59  967.41   127.9  944.98   147.6  941.66
   295.1   881.1   334.4  869.93     364  855.22   393.5  835.38   403.3  832.53
   472.2  778.76   491.8  770.31   521.3  751.71   590.2  749.89   626.9  743.51
   639.4   741.9   641.9  742.05   747.6  752.33   806.6  781.76   855.8  786.17
   914.8  825.58   934.5  830.79   993.5  865.35  1003.3  866.07  1013.2  871.72
    1082   922.3  1101.7  928.18  1170.6  966.96  1190.2   972.7  1249.2 1008.67
#Mann= 3 , 0 , 0
       0     .06       0   626.9    .045       0   641.9     .06       0
Bank Sta=626.9,641.9
XS Rating Curve= 0 ,0
Exp/Cntr=0.3,0.1

Type RM Length L Ch R = 1 ,13405.3 ,591.6,584.8,578.2
XS GIS Cut Line= 2
     1698993.958      311740.491     1698264.351       312715.16
#Sta/Elev= 30
       0 1052.98    39.3 1025.33    49.1 1022.88    58.9 1016.34    78.6  998.92
   127.6  966.22   157.1   952.9   225.8  904.91   245.5  897.53   314.2  849.18
   333.8  842.56   412.4  784.93     432  778.85   461.5  759.31   500.8  748.35
     648  746.83   692.4  737.25   697.1  736.93   707.4  737.36   736.4  743.66
   814.9  746.73   883.7  793.52   893.5  796.67   981.8   854.2  1001.5  861.04
  1060.4  901.89  1089.9  912.42  1168.4  951.11    1188  956.65  1217.5     971
#Mann= 3 , 0 , 0
       0     .06       0   692.4    .045       0   707.4     .06       0
Bank Sta=692.4,707.4
XS Rating Curve= 0 ,0
Exp/Cntr=0.3,0.1

Type RM Length L Ch R = 1 ,12820.5 ,442.9,443.4,443.8
XS GIS Cut Line= 2
     1698330.229       311348.31     1697883.874      312544.736
#Sta/Elev= 30
       0  982.48    58.9  948.52    78.6  943.46   137.5  914.19   157.2  909.79
   206.3  888.04   255.4  876.55   314.3   847.8   324.2  846.99   530.4  743.36
   618.8  741.91   665.6  732.44   677.8  731.23   680.6  732.01   726.9  750.45
   746.5  749.43     776  738.67   825.1  748.52   844.8  763.15   884.1  801.99
   903.7  810.31   962.6  851.69   982.3  858.41  1041.2  894.34  1060.9  900.04
  1129.6  940.31  1149.3  946.22    1218   990.9  1227.9  991.54    1277 1026.58
#Mann= 3 , 0 , 0
       0     .06       0   665.6    .045       0   680.6     .06       0
Bank Sta=665.6,680.6
XS Rating Curve= 0 ,0
Exp/Cntr=0.3,0.1

Type RM Length L Ch R = 1 ,12377.1 ,407.7,406.1,404.6
XS GIS Cut Line= 2
     1697940.536      311191.762     1697448.712      312440.011
#Sta/Elev= 30
       0 1039.65      49  1010.2   107.7  951.96   156.7  918.72   195.9  893.79
   215.4  887.96     284  849.18   293.8   849.1   362.3  802.53   381.9  796.56
   440.7  758.49   528.8  735.88   646.3  735.52   744.3  727.63   753.3  727.97
   768.3  731.95   832.4  735.13   861.8  749.14     901  755.92   940.1  784.88
   959.7  792.31  1018.5  838.93  1038.1  845.84  1096.8  893.08    1136  905.93
  1165.4  930.19  1224.1  947.96  1273.1  968.85  1292.7  971.68  1341.6  992.29
#Mann= 3 , 0 , 0
       0     .06       0   753.3    .045       0   768.3     .06       0
Bank Sta=753.3,768.3
XS Rating Curve= 0 ,0
Exp/Cntr=0.3,0.1

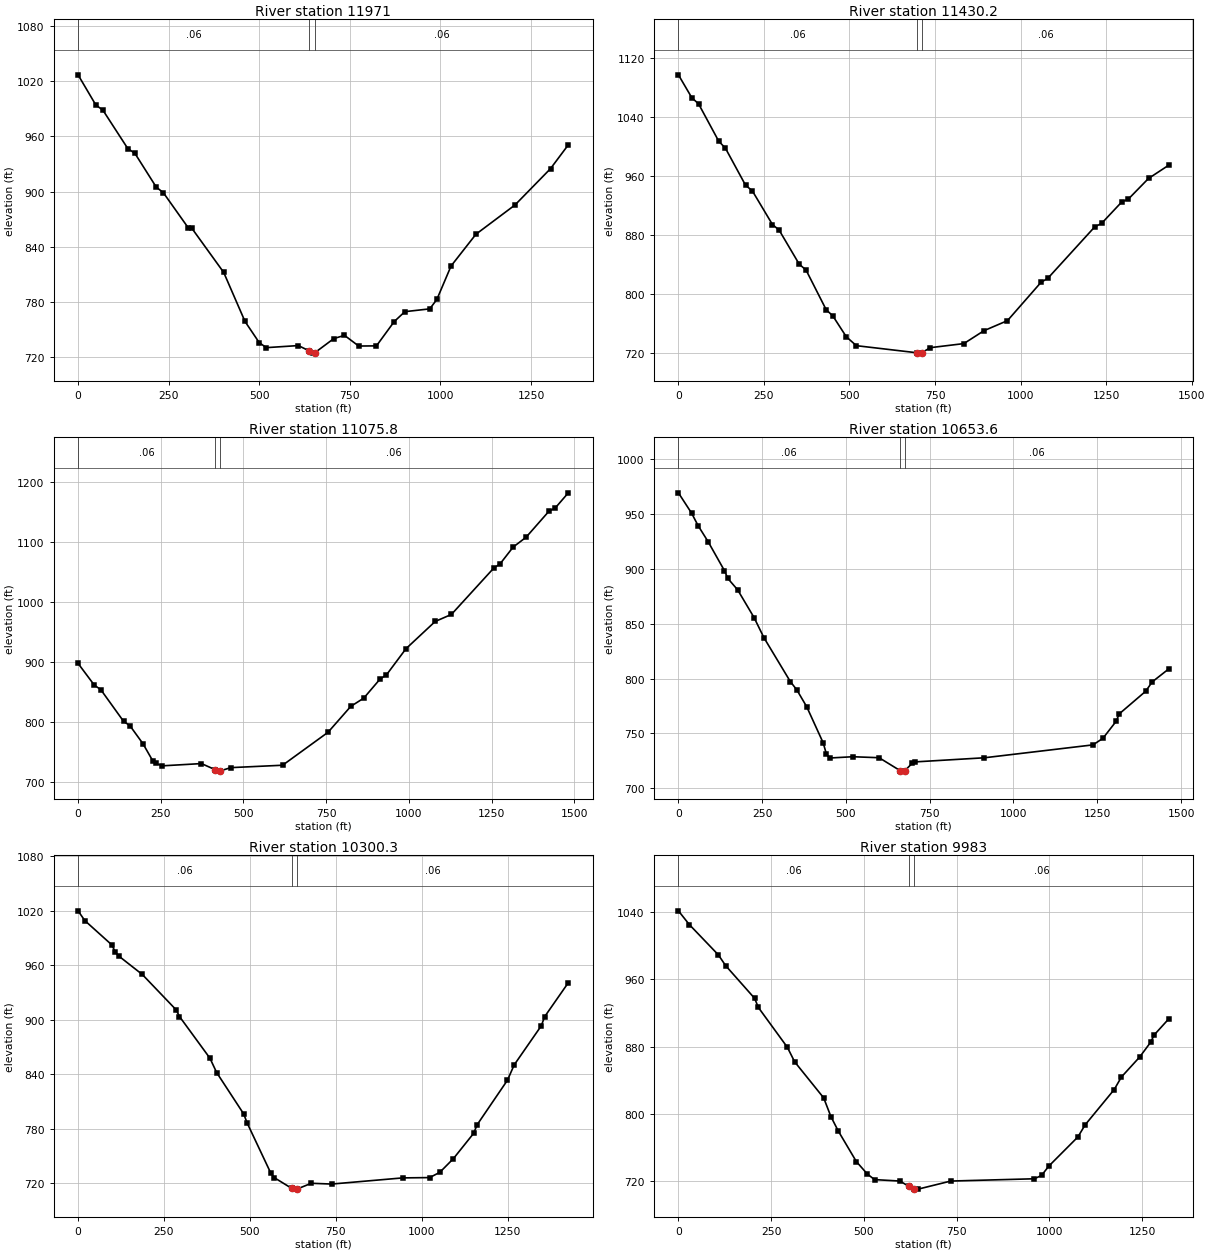
Type RM Length L Ch R = 1 ,11971   ,544.4,540.8,537.2
XS GIS Cut Line= 2
     1697527.688      311058.605     1697115.525      312347.043
#Sta/Elev= 30
       0 1027.05      49  994.26    68.6  988.61   137.2  946.89   156.8   941.7
   215.7  904.98   235.3  898.89   303.9  860.76   313.7  860.33   401.9  812.17
   460.7  758.81   499.9  735.85   519.5  730.36   607.8  732.61   638.1  726.81
     647   724.4   653.1  724.77   705.8  740.24   735.2  743.72   774.4   732.1
   823.4   732.3   872.4  758.73   901.8  769.49   970.5  772.54   990.1  782.81
  1029.3   819.2  1097.9  853.69  1205.7  885.52  1303.7  925.04  1352.8  950.93
#Mann= 3 , 0 , 0
       0     .06       0   638.1    .045       0   653.1     .06       0
Bank Sta=638.1,653.1
XS Rating Curve= 0 ,0
Exp/Cntr=0.3,0.1

Type RM Length L Ch R = 1 ,11430.2 ,347.2,354.4,361.6
XS GIS Cut Line= 2
     1696908.455      310874.382      1696695.82      312291.303
#Sta/Elev= 30
       0 1097.59    39.2  1066.5    58.9 1058.24   117.8  1007.6   137.4   998.1
   196.3  947.77   215.9  940.32   274.8  894.56   294.4  886.92   353.3   840.6
   372.9  832.91   431.8  779.03   451.4   770.5   490.7  742.28   520.1   730.2
   697.2  720.57   706.6  720.09   712.2  720.91     736  727.49   834.2  733.02
     893  750.51   961.7  764.17  1059.9  816.22  1079.5  821.52  1216.9  891.47
  1236.5  895.94  1295.4  925.02    1315  929.07  1373.9  957.03  1432.8  974.96
#Mann= 3 , 0 , 0
       0     .06       0   697.2    .045       0   712.2     .06       0
Bank Sta=697.2,712.2
XS Rating Curve= 0 ,0
Exp/Cntr=0.3,0.1

Type RM Length L Ch R = 1 ,11075.8 ,405.5,422.2,439
XS GIS Cut Line= 2
     1696660.461      311080.436     1695990.206      312402.393
#Sta/Elev= 30
       0  897.94    49.1  861.75    68.7  854.24   137.4  801.59     157  794.03
   196.3  764.11   225.8  735.68   235.6  731.24   255.2  727.31     373  731.05
   413.6  721.15   422.1  718.48   428.6   718.6   461.3  724.29   618.4   728.3
   755.8  783.21   824.5  826.33   863.8  840.07   912.9  871.75   932.5   878.9
   991.4  922.38  1079.7  967.77  1128.8   979.5  1256.4 1056.45    1276 1063.79
  1315.3 1091.61  1354.6 1108.12  1423.3 1151.19  1442.9 1156.93  1482.2 1182.04
#Mann= 3 , 0 , 0
       0     .06       0   413.6    .045       0   428.6     .06       0
#XS Ineff= 2 , 0
           371.3  730.92
Permanent Ineff=
       F       F
Bank Sta=413.6,428.6
XS Rating Curve= 0 ,0
Exp/Cntr=0.3,0.1

Type RM Length L Ch R = 1 ,10653.6 ,352.6,353.3,353.9
XS GIS Cut Line= 2
     1696746.139      311001.993     1695376.304      311516.125
#Sta/Elev= 30
       0  968.98    39.3  950.53    58.9  939.04    88.4  924.68   137.5  898.11
   147.3  891.15   176.8   880.7   225.8  855.48   255.3  837.13   333.9  797.29
   353.5  789.62     383  774.28   432.1  741.44   441.9  731.08   451.7  727.68
   520.4  728.84     599  727.94   661.3  716.28   667.7  715.74   676.3   716.3
   697.2  722.73     707  724.15   913.2  727.89  1237.3  739.63  1266.8  745.57
    1306  760.95  1315.8  767.89  1394.4   788.4    1414  796.94  1463.1  808.69
#Mann= 3 , 0 , 0
       0     .06       0   661.3    .045       0   676.3     .06       0
Bank Sta=661.3,676.3
XS Rating Curve= 0 ,0
Exp/Cntr=0.3,0.1

Type RM Length L Ch R = 1 ,10300.3 ,318.2,317.3,316.3
XS GIS Cut Line= 2
     1696670.964       310687.74     1695321.143      311148.796
#Sta/Elev= 30
       0 1019.99    19.7 1009.23    98.4  982.44   108.2  974.69     118  970.35
   186.9  949.93   285.3  911.03   295.1  903.64   383.6   857.8   403.3  841.93
     482  796.34   491.9  786.49   560.7   731.3   570.6  726.31   621.7  714.46
   629.6  713.62   636.7  713.65   678.8  720.06   737.8   719.2   944.4  725.98
  1023.1  726.33  1052.6  732.16  1091.9  747.13    1151  775.08  1160.8  784.33
  1249.3  833.53    1269  850.45  1347.7   893.4  1357.5  903.45  1426.4  940.87
#Mann= 3 , 0 , 0
       0     .06       0   621.7    .045       0   636.7     .06       0
Bank Sta=621.7,636.7
XS Rating Curve= 0 ,0
Exp/Cntr=0.3,0.1

Type RM Length L Ch R = 1 ,9983    ,452.2,451.7,451.1
XS GIS Cut Line= 2
     1696552.063      310365.621     1695320.271       310845.44
#Sta/Elev= 30
       0 1041.87    29.4 1025.48   107.7  989.35   127.3  976.55   205.6  937.44
   215.4  926.73   293.8  879.11   313.4  861.82   391.7  818.79   411.3  796.37
   430.9  779.39   479.8  742.83   509.2  728.07   528.8  721.32   597.3  719.59
   620.5  713.48   635.5   710.5   646.3  709.96   734.4  719.59   959.6   722.3
   979.2  726.28   998.8  737.47  1077.1  772.18  1096.7  786.63  1175.1  828.76
  1194.6  843.75  1243.6  867.46    1273  884.95  1282.8  893.84  1321.9   912.9
#Mann= 3 , 0 , 0
       0     .06       0   620.5    .045       0   635.5     .06       0
Bank Sta=620.5,635.5
XS Rating Curve= 0 ,0
Exp/Cntr=0.3,0.1

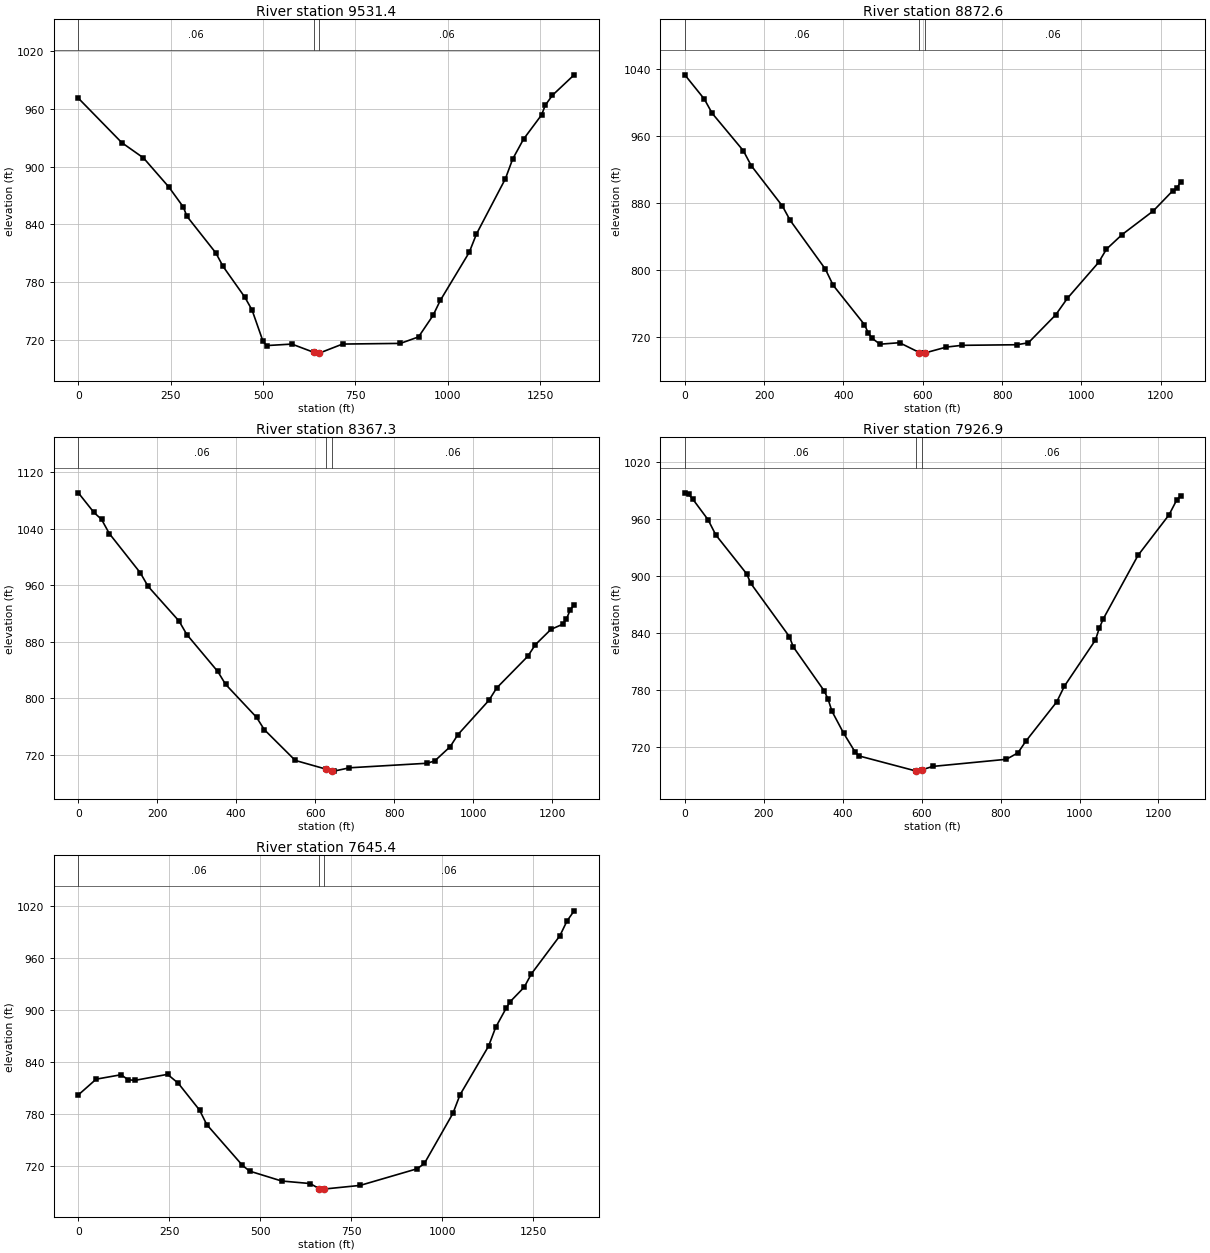
Type RM Length L Ch R = 1 ,9531.4  ,659.3,658.7,658.2
XS GIS Cut Line= 2
     1696385.913      309932.675     1695147.477      310449.738
#Sta/Elev= 30
       0   971.3   117.6  925.06   176.3  909.18   244.9  878.96   284.1  858.17
   293.9   848.5   372.2  810.37   391.8  796.33   450.6  764.41   470.2  751.03
   499.6  718.75   509.4  714.06     578  715.63   637.7  706.98   646.5  706.22
   652.7   706.3   715.1  715.64   871.8  716.34   920.8  723.08     960  745.38
   979.6  760.96    1058     811  1077.6  830.09  1155.9  887.53  1175.5  907.96
  1204.9  928.65  1253.9  953.93  1263.7  963.92  1283.3  974.35    1342  995.58
#Mann= 3 , 0 , 0
       0     .06       0   637.7    .045       0   652.7     .06       0
Bank Sta=637.7,652.7
XS Rating Curve= 0 ,0
Exp/Cntr=0.3,0.1

Type RM Length L Ch R = 1 ,8872.6  ,504.7,505.3,505.9
XS GIS Cut Line= 2
     1696105.323      309321.139     1694964.039      309830.673
#Sta/Elev= 30
       0 1033.51    49.2 1004.56    68.9  987.63   147.6  942.87   167.3  925.17
     246  876.81   265.7  859.67   354.3  801.52     374  782.19   452.7  735.31
   462.6  725.18   472.4  718.75   492.1   711.8   541.3  713.57   591.4  701.84
   600.3  701.13   606.4  701.48   659.4  708.36   698.7  710.44   836.5  711.14
     866  713.43   934.9  746.79   964.5  766.64  1043.2  809.52  1062.9  825.29
  1102.2  842.66    1181  870.98  1230.2  895.11    1240  897.85  1249.9  905.55
#Mann= 3 , 0 , 0
       0     .06       0   591.4    .045       0   606.4     .06       0
Bank Sta=591.4,606.4
XS Rating Curve= 0 ,0
Exp/Cntr=0.3,0.1

Type RM Length L Ch R = 1 ,8367.3  ,440.5,440.4,440.3
XS GIS Cut Line= 2
     1695968.346      308851.424     1694807.265      309331.017
#Sta/Elev= 30
       0 1090.92    39.3 1063.26    58.9 1053.21    78.5 1033.21     157  977.62
   176.7  958.48   255.2  909.29   274.8  890.27   353.3  837.88   372.9  819.82
   451.5     773   471.1  755.57   549.6  711.93   627.4  699.63   642.4  697.25
   647.7  696.78     687  701.51   883.3  707.92   902.9  711.19   942.2  731.46
   961.8  748.54  1040.3  797.08    1060  814.61  1138.5   859.3  1158.1  875.95
  1197.4  897.53  1226.8  904.71  1236.6  912.14  1246.4  925.37  1256.2  932.18
#Mann= 3 , 0 , 0
       0     .06       0   627.4    .045       0   642.4     .06       0
Bank Sta=627.4,642.4
XS Rating Curve= 0 ,0
Exp/Cntr=0.3,0.1

Type RM Length L Ch R = 1 ,7926.9  ,282.4,281.5,280.5
XS GIS Cut Line= 2
      1695738.33       308469.43     1694578.918      308953.042
#Sta/Elev= 30
       0  987.63     9.8  986.03    19.6  981.33    58.9   959.3    78.5  943.29
     157  902.13   166.8  892.42     265   836.1   274.8  825.28   353.3  778.85
   363.1  770.05   372.9  757.39   402.4   734.3   431.8  714.26   441.6  710.33
   586.9  694.34   601.9  695.87   628.1   699.3   814.6  706.81     844  713.58
   863.7  725.71   942.2  767.24   961.8  783.93  1040.3  832.44  1050.1   844.9
    1060  854.64  1148.3  921.76  1226.8  964.41  1246.4  980.17  1256.2  984.54
#Mann= 3 , 0 , 0
       0     .06       0   586.9    .045       0   601.9     .06       0
Bank Sta=586.9,601.9
XS Rating Curve= 0 ,0
Exp/Cntr=0.3,0.1

Type RM Length L Ch R = 1 ,7645.4  ,816.9,814.6,812.4
XS GIS Cut Line= 2
     1695684.419      308157.729     1694449.806      308734.517
#Sta/Elev= 30
       0  801.78      49     820   117.6  825.12   137.2  819.18   156.9   818.7
   245.1  825.58   274.5  815.34   333.3  784.16   352.9  767.51     451  720.32
   470.6  713.68   558.8  702.21   637.2  699.28   661.3  693.49   666.6  692.82
   676.3  692.95   774.5  697.13   931.3  716.39     951  722.47  1029.4  780.37
    1049   801.9  1127.4  858.12    1147  879.94  1176.4  902.53  1186.2  909.34
  1225.4  926.38  1245.1  941.75  1323.5  985.86  1343.1 1003.01  1362.7 1014.69
#Mann= 3 , 0 , 0
       0     .06       0   661.3    .045       0   676.3     .06       0
Bank Sta=661.3,676.3
XS Rating Curve= 0 ,0
Exp/Cntr=0.3,0.1