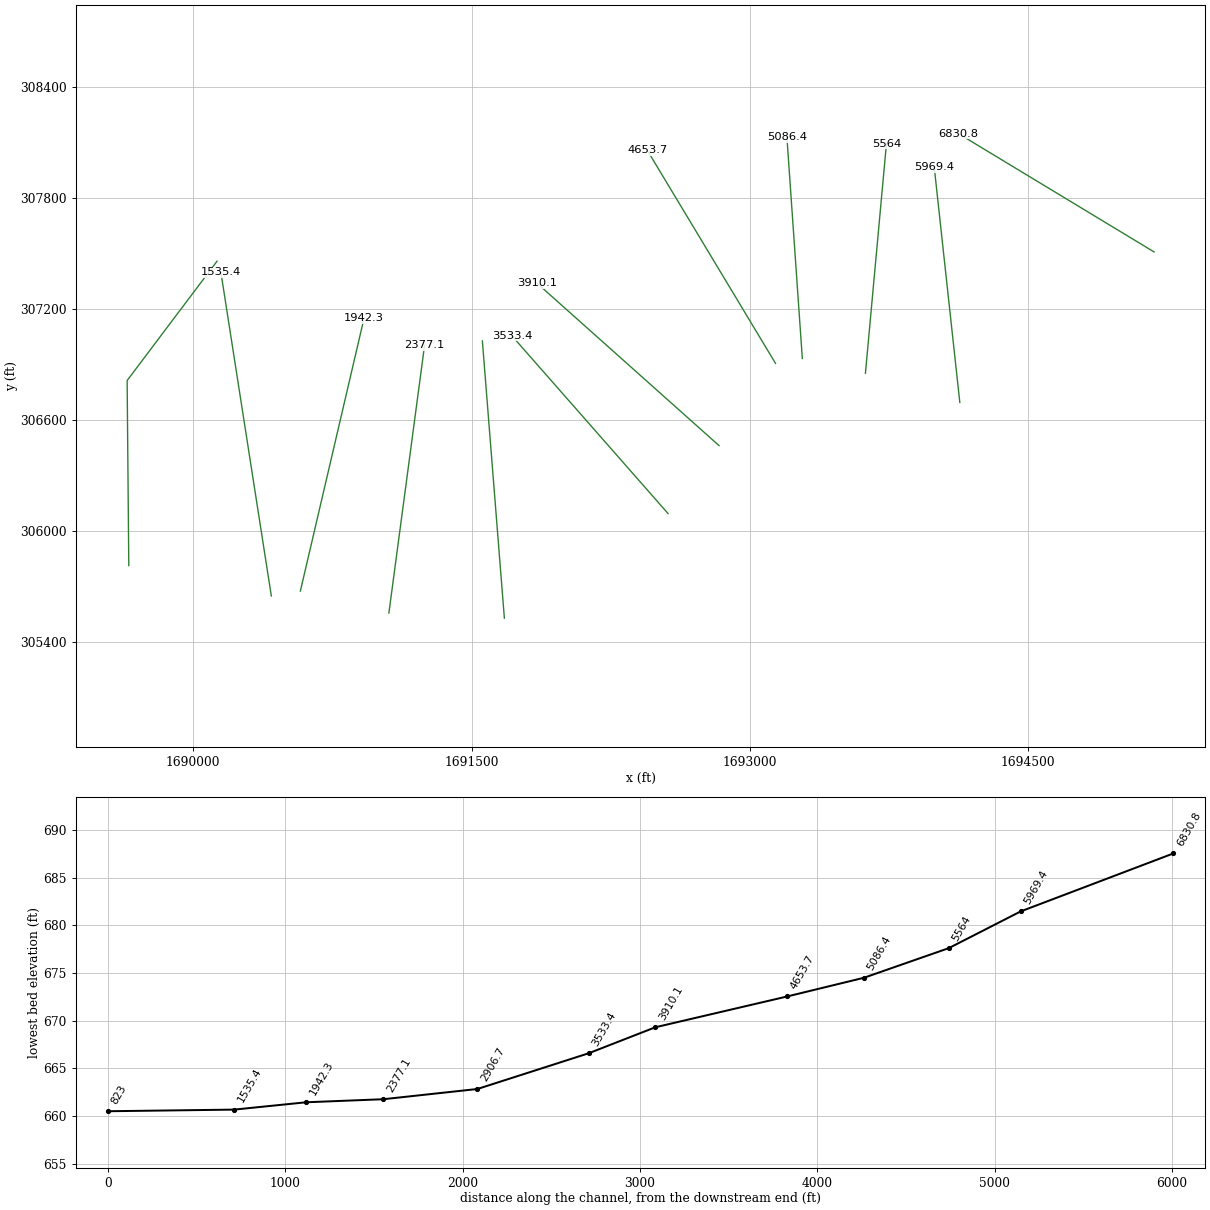
HEC-RAS study DINGESSRN.prj: DINGESSRN

--- DINGESSRN.g01 (geometry) --- (continued)

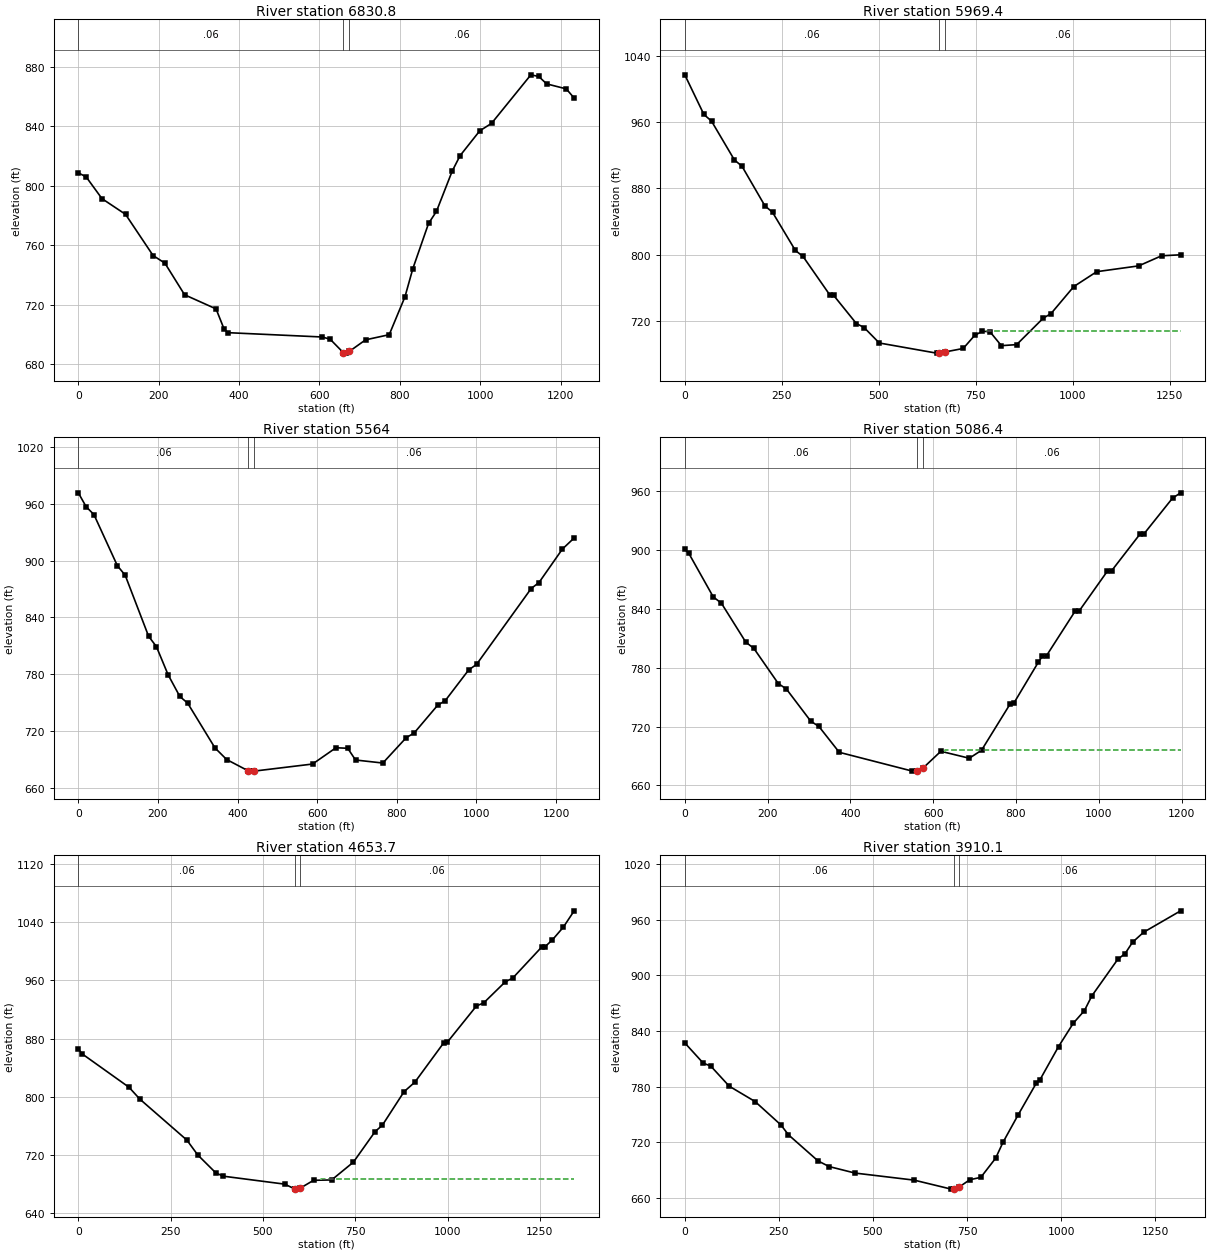
Type RM Length L Ch R = 1 ,6830.8  ,882.3,861.4,840.6
XS GIS Cut Line= 2
     1695179.311      307508.706      1694124.14      308148.211
#Sta/Elev= 30
       0  808.72    19.6  805.94    58.8  791.37   117.5   780.8     186  753.14
   215.4  748.01   264.4  726.76   342.7  717.27   362.3     704   372.1  701.29
   607.1  698.38   626.7  696.87   659.1  687.95   665.9  687.54   674.1  688.65
   714.8  696.48   773.6  699.93   812.8   725.4   832.4  744.35   871.5  774.72
   891.1  782.78   930.3  809.87   949.9  820.24   998.8  836.92  1028.2  841.96
  1126.1  874.58  1145.7  873.48  1165.3   868.5  1214.2  865.13  1233.8  858.96
#Mann= 3 , 0 , 0
       0     .06       0   659.1    .045       0   674.1     .06       0
Bank Sta=659.1,674.1
XS Rating Curve= 0 ,0
Exp/Cntr=0.3,0.1

Type RM Length L Ch R = 1 ,5969.4  ,410,405.5,401
XS GIS Cut Line= 2
     1694132.123      306695.805     1693994.338      307965.936
#Sta/Elev= 30
       0 1016.91    49.1   969.2    68.8  961.13   127.8  914.34   147.4  906.68
   206.4  859.01     226  851.23     285  805.17   304.6     798   373.4  751.78
   383.3  751.21   442.2  717.06   461.9  712.34   501.2  693.67   648.6  681.46
   655.5  681.55   670.5  682.86   717.4  687.08   746.9  702.83   766.6  707.82
   786.2  707.31   815.7  690.46     855   691.7   923.8   723.7   943.4  728.98
  1002.4  761.72  1061.4  779.63  1169.5  786.62  1228.4  798.78  1277.6  799.98
#Mann= 3 , 0 , 0
       0     .06       0   655.5    .045       0   670.5     .06       0
#XS Ineff= 2 , 0
                          775.02          707.89
Permanent Ineff=
       F       F
Bank Sta=655.5,670.5
XS Rating Curve= 0 ,0
Exp/Cntr=0.3,0.1

Type RM Length L Ch R = 1 ,5564    ,473.8,477.6,481.3
XS GIS Cut Line= 2
      1693623.39      306853.688     1693736.681       308093.78
#Sta/Elev= 30
       0  971.69    19.6  956.99    39.2   948.7      98  894.72   117.7  884.57
   176.5  820.11   196.1   809.2   225.5   779.4   254.9  756.51   274.5   749.5
   343.2  702.13   372.6  689.84   427.3   677.8   441.2  677.61   442.3  677.66
   588.3  685.11   647.1  702.33   676.6  701.75   696.2  689.36   764.8  686.16
   823.6     713   843.2   717.8   902.1  747.04   921.7  752.18   980.5   784.6
  1000.1  790.36  1137.4  870.59    1157   876.9  1215.8  912.29  1245.3     924
#Mann= 3 , 0 , 0
       0     .06       0   427.3    .045       0   442.3     .06       0
#XS Ineff= 2 , 0
                          657.22          702.04
Permanent Ineff=
       F       F
Bank Sta=427.3,442.3
XS Rating Curve= 0 ,0
Exp/Cntr=0.3,0.1

Type RM Length L Ch R = 1 ,5086.4  ,420.6,432.7,444.9
XS GIS Cut Line= 2
     1693283.226      306933.232     1693200.127      308128.088
#Sta/Elev= 30
       0   900.9     9.8  896.72    68.7  852.37    88.4  845.92   147.3  806.19
   166.9  799.74   225.8  763.93   245.4  758.34   304.3  725.49     324  720.08
   373.1  693.72   549.8  674.51   559.7  674.53   574.7  677.36   618.5  694.75
   687.2  687.67   716.7  695.76   785.4  742.75   795.2  744.18   854.1  785.78
     864  791.93   873.8  792.39   942.5  837.58   952.3  837.77    1021  878.78
  1030.8   878.9  1099.6  916.49  1109.4  916.81  1178.1  953.14  1197.7  958.58
#Mann= 3 , 0 , 0
       0     .06       0   559.7    .045       0   574.7     .06       0
#XS Ineff= 2 , 0
                          628.17          695.59
Permanent Ineff=
       F       F
Bank Sta=559.7,574.7
XS Rating Curve= 0 ,0
Exp/Cntr=0.3,0.1

Type RM Length L Ch R = 1 ,4653.7  ,738.3,743.6,748.8
XS GIS Cut Line= 2
     1693138.689      306906.737     1692447.424      308057.822
#Sta/Elev= 30
       0  865.59     9.8  859.08   137.2  812.89   166.6  796.53     294  740.07
   323.4  719.64   372.4  694.88     392  690.42   558.6  679.44   585.5     673
     588  672.55   600.5  673.75     637  684.71     686  685.21   744.9  709.73
   803.7  751.84   823.3  760.59   882.1  806.82   911.5  820.01   989.9  874.41
   999.7  875.28  1078.1  924.88  1097.7  929.08  1156.5   958.3  1176.1  963.16
  1254.5 1005.92  1264.3  1006.7  1283.9 1016.04  1313.3 1033.37  1342.7 1055.95
#Mann= 3 , 0 , 0
       0     .06       0   585.5    .045       0   600.5     .06       0
#XS Ineff= 2 , 0
                          655.98          686.18
Permanent Ineff=
       F       F
Bank Sta=585.5,600.5
XS Rating Curve= 0 ,0
Exp/Cntr=0.3,0.1

Type RM Length L Ch R = 1 ,3910.1  ,379.5,376.7,373.9
XS GIS Cut Line= 2
     1692834.227      306462.611     1691852.037      307340.633
#Sta/Elev= 30
       0  827.16    49.2  805.24    68.8  802.24     118  780.47   186.8  763.85
   255.6  738.54   275.3     728   353.9   699.8   383.4  693.69   452.2  686.66
   609.6  679.02   707.9  669.32   714.8  669.36   729.8  671.81     757  679.41
   786.5  682.04   825.8  702.66   845.5  719.89   884.8  748.82     934  783.79
   943.8  787.47     993  823.19  1032.3  848.45  1061.8  862.03  1081.5  877.92
  1150.3  917.34    1170  923.66  1189.6   935.8  1219.1  946.62  1317.4  969.73
#Mann= 3 , 0 , 0
       0     .06       0   714.8    .045       0   729.8     .06       0
Bank Sta=714.8,729.8
XS Rating Curve= 0 ,0
Exp/Cntr=0.3,0.1

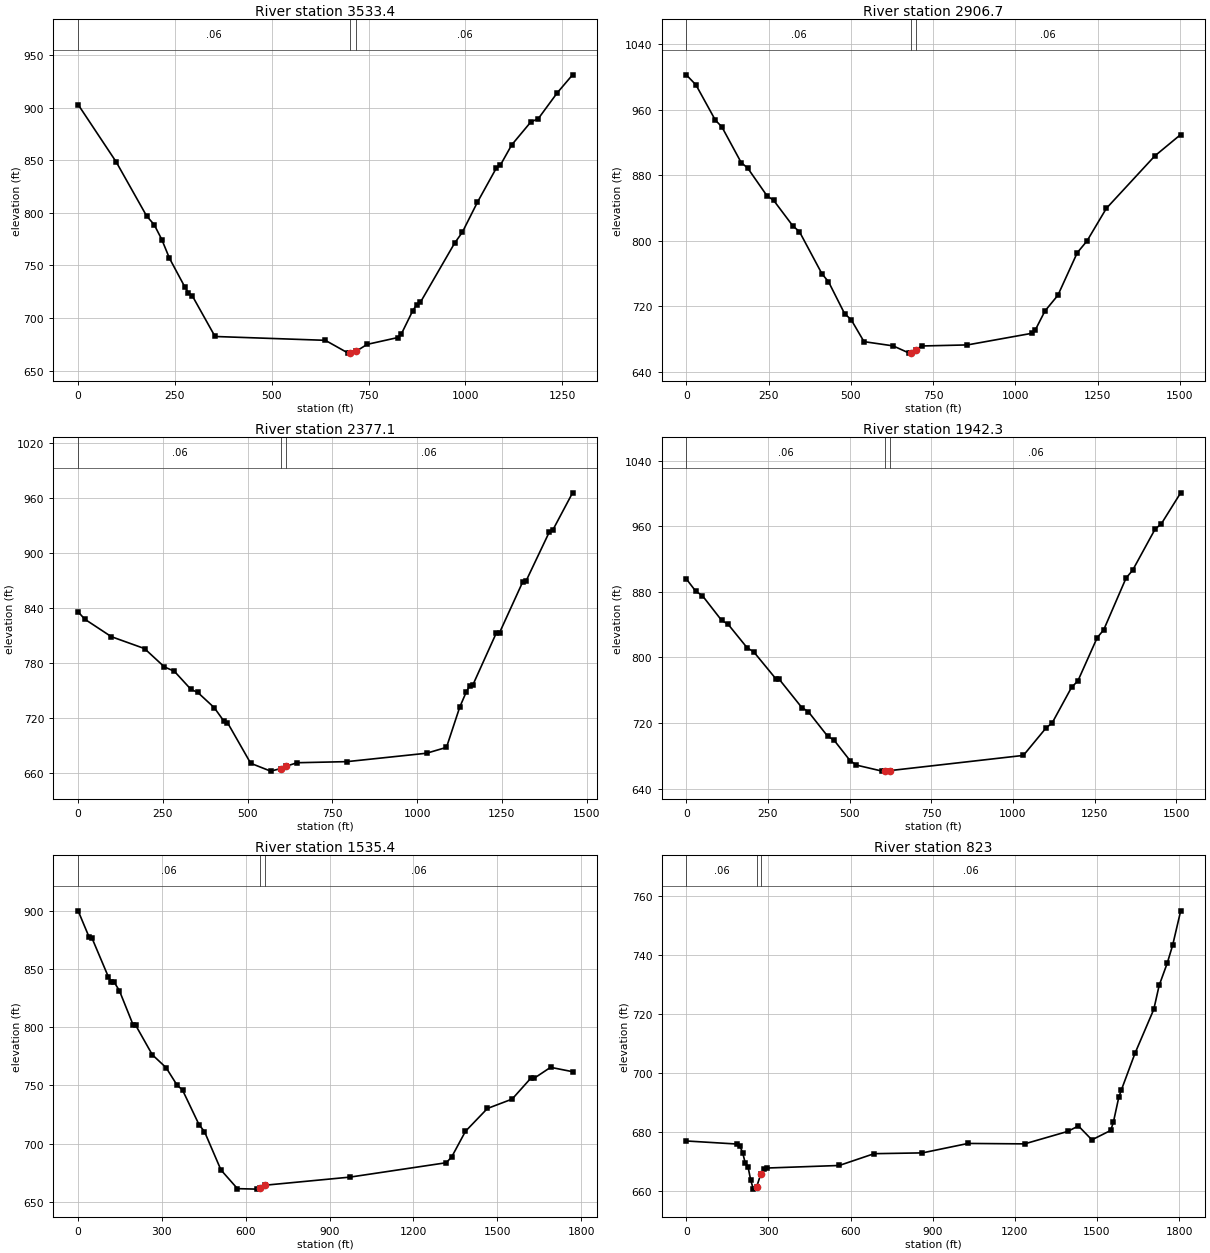
Type RM Length L Ch R = 1 ,3533.4  ,643.4,626.8,610.1
XS GIS Cut Line= 2
     1692559.344      306095.613     1691717.467      307055.905
#Sta/Elev= 30
       0  903.02    98.2  848.55   176.8  797.13   196.5  788.73   216.1  774.66
   235.8  756.89   275.1  729.86   284.9     724   294.7  721.23   353.6  682.42
   638.5  678.77   697.5  666.59   703.3  666.67   718.3  668.44   746.6  674.93
   825.2  681.36     835  684.95   864.5  707.08   874.3  712.57   884.1  714.97
   972.5  771.28   992.2  781.49  1031.5  810.25  1080.6  842.94  1090.4   845.3
  1119.9  864.69    1169  886.37  1188.7  889.72  1237.8  914.36  1277.1  931.35
#Mann= 3 , 0 , 0
       0     .06       0   703.3    .045       0   718.3     .06       0
Bank Sta=703.3,718.3
XS Rating Curve= 0 ,0
Exp/Cntr=0.3,0.1

Type RM Length L Ch R = 1 ,2906.7  ,532.1,529.6,527.1
XS GIS Cut Line= 2
     1691677.069      305530.369     1691558.508      307027.837
#Sta/Elev= 30
       0 1002.85    29.4  990.58    88.4  947.46     108  939.36   166.9  895.63
   186.5  889.01   245.4  854.99   265.1  849.71     324  818.18   343.6  811.44
   412.4  759.66     432  750.17   481.1  711.06   500.7   703.9     540  676.88
   628.4  671.71   677.4  662.85   682.1  663.54   697.1  667.27   716.7  671.59
   854.2  672.88  1050.5   687.1  1060.3     691  1089.8   714.3  1129.1  733.53
    1188  785.56  1217.4   799.8  1276.3  839.67  1423.6  903.77  1502.2  929.88
#Mann= 3 , 0 , 0
       0     .06       0   682.1    .045       0   697.1     .06       0
Bank Sta=682.1,697.1
XS Rating Curve= 0 ,0
Exp/Cntr=0.3,0.1

Type RM Length L Ch R = 1 ,2377.1  ,437.2,434.8,432.5
XS GIS Cut Line= 2
     1691054.599        305558.6     1691246.928      307004.181
#Sta/Elev= 30
       0  835.46    19.6  827.46    97.9   808.4   195.8  795.42   254.5  775.38
   283.8  770.67   332.8  750.87   352.4  747.74   401.3  731.03   430.6  715.96
   440.4  714.73   508.9  670.35   567.7  661.78     598  664.57     613  667.09
     646  670.94   792.8  672.13  1027.7   681.3  1086.4  687.68  1125.6  731.67
  1145.1  748.39  1154.9  754.81  1164.7  756.16  1233.2  812.27    1243   812.8
  1311.5  868.32  1321.3  869.25  1389.8  922.62  1399.6   924.4  1458.3  965.26
#Mann= 3 , 0 , 0
       0     .06       0     598    .045       0     613     .06       0
Bank Sta=598,613
XS Rating Curve= 0 ,0
Exp/Cntr=0.3,0.1

Type RM Length L Ch R = 1 ,1942.3  ,398.2,406.9,415.5
XS GIS Cut Line= 2
     1690577.414      305676.973     1690920.804      307150.911
#Sta/Elev= 30
       0  895.83    29.5  880.54    49.1  875.51   108.1   845.3   127.8  840.58
   186.7  811.65   206.4  806.91   275.2  773.55     285  773.16   353.8  738.91
   373.4  734.02   432.4  704.19   452.1  699.34   501.2  674.37   520.8  668.81
   599.5  661.46   609.5  661.56   624.5  662.15  1031.9  680.62  1100.7  713.81
  1120.3  720.44  1179.3  763.52  1198.9   771.6  1257.9  824.23  1277.6  833.56
  1346.3  896.92    1366  906.14  1434.8  956.26  1454.4  963.12  1513.4 1000.71
#Mann= 3 , 0 , 0
       0     .06       0   609.5    .045       0   624.5     .06       0
Bank Sta=609.5,624.5
XS Rating Curve= 0 ,0
Exp/Cntr=0.3,0.1

Type RM Length L Ch R = 1 ,1535.4  ,716.6,712.4,708.3
XS GIS Cut Line= 2
     1690420.857      305650.431     1690148.966      307398.989
#Sta/Elev= 30
       0  900.53    39.3  877.86    49.2  877.25   108.1  843.66     118  839.44
   127.8  839.45   147.5  831.82   196.6  802.34   206.4  801.72   265.4  776.51
   314.6  765.43   353.9  750.38   373.6   746.1   432.6   716.3   452.2  710.23
   511.2  677.19   570.2   661.1     639  660.69   652.2   661.5   667.2  664.02
   973.3  671.06  1317.4  683.44    1337  688.44  1386.2   710.5  1464.8   730.2
  1553.3  738.28  1622.1  756.83  1631.9   756.2  1690.9  765.66  1769.6   761.9
#Mann= 3 , 0 , 0
       0     .06       0   652.2    .045       0   667.2     .06       0
Bank Sta=652.2,667.2
XS Rating Curve= 0 ,0
Exp/Cntr=0.3,0.1

Type RM Length L Ch R = 1 ,823     ,829.6,823,816.4
XS GIS Cut Line= 3
     1689652.497      305814.376     1689643.611      306814.066
     1690127.905       307458.31
#Sta/Elev= 30
       0  676.89   186.2  675.84     196  675.11   205.8  672.97   215.6  669.29
   225.4  668.18   235.2  663.63     245  660.52   257.5   661.4   272.5  665.75
   284.2  667.52     294  667.69   558.7  668.56   686.1  672.57   862.5  672.84
  1029.2  676.05  1235.6   675.9  1392.9  680.13  1432.2  681.99  1481.4  677.27
  1550.2  680.48    1560  683.33  1579.6  691.74  1589.5  694.34  1638.6  706.64
  1707.4  721.62  1727.1  729.78  1756.6  737.34  1776.2  743.39  1805.7  755.12
#Mann= 3 , 0 , 0
       0     .06       0   257.5    .045       0   272.5     .06       0
Bank Sta=257.5,272.5
XS Rating Curve= 0 ,0
Exp/Cntr=0.3,0.1

Chan Stop Cuts=-1
Use User Specified Reach Order=0
Composite Channel Slope=5